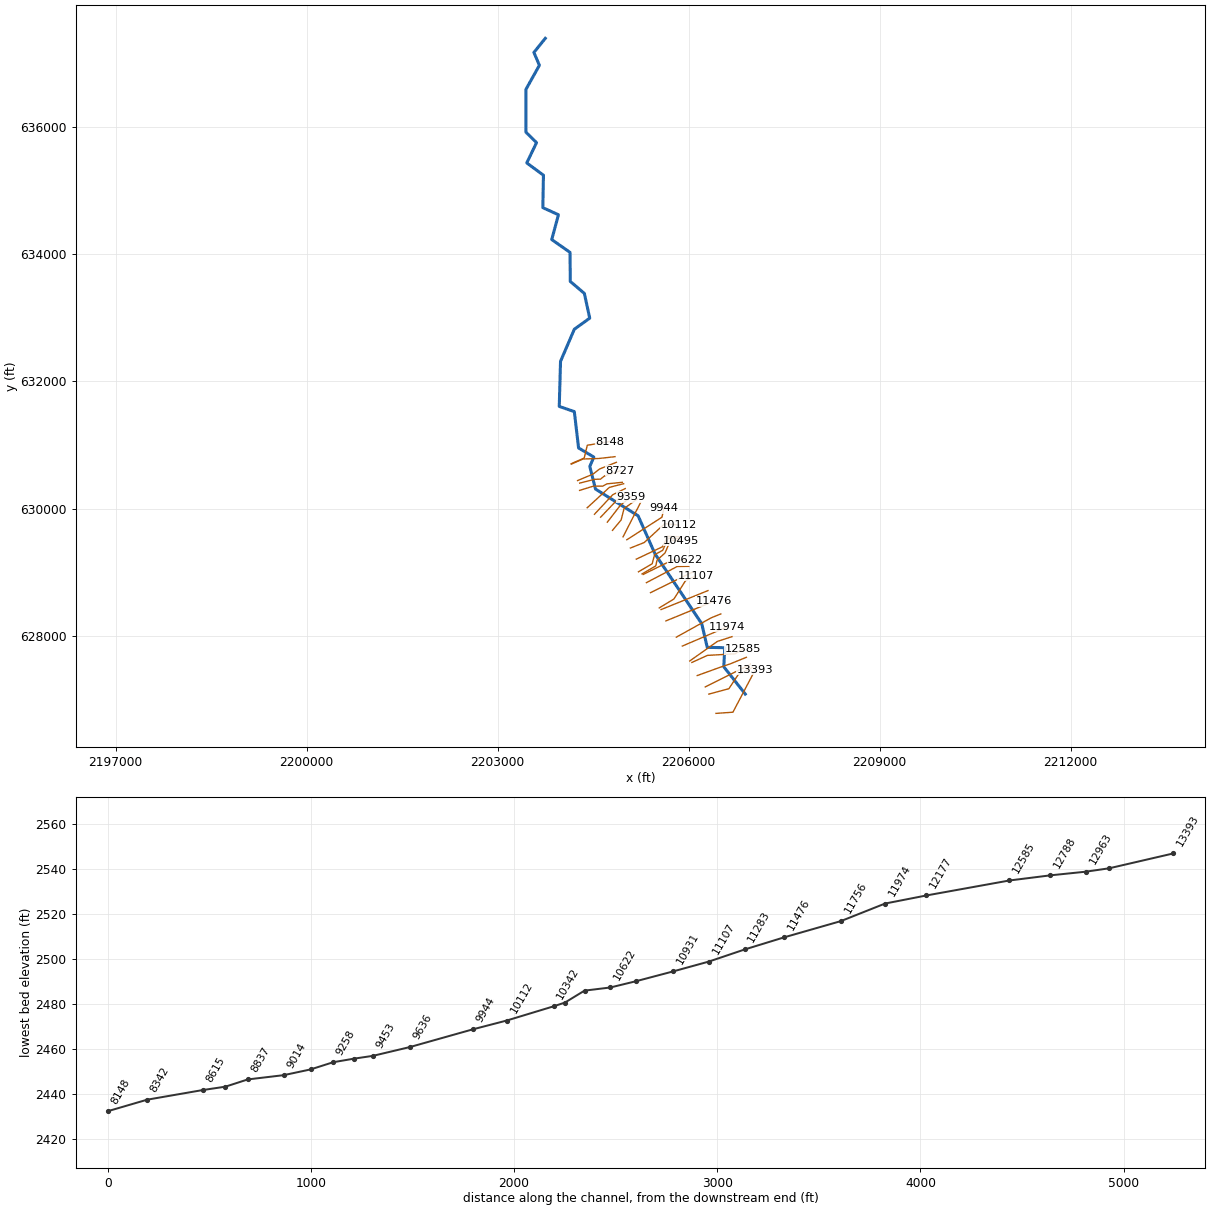
--- BEARCMPRN.prj (project) ---

Proj Title=BEARCMPRN
Current Plan=p01
Default Exp/Contr=0,0
English Units
Geom File=g01
Flow File=f01
Plan File=p01
Background Map Layer=Inundation Boundary (P100yr Value_0)
BEGIN DESCRIPTION:
----------MODEL BY WOOD PLC 2022----------
AFH study
Randolph County, WV
HEC-RAS Version: RAS 6.2
Vertical Datum: NAVD88
Projection: NAD 1983 StatePlane West Virginia S FIPS 4702 (US Feet)
Terrain: 1-meter LIDAR (FEMA Region III 3DEP collected 2016-2018)
Land Use: 2019 NLCD
Hydrologic Method:
WV SIR2010-5033 regression equations
Additional Model Notes:
Downstream boundary is beyond county boundary
END DESCRIPTION:
DSS Export Rating Curves= 0
DSS Export Rating Curve Sorted= 0
DSS Export Volume Flow Curves= 0
DXF OffsetX= 0
DXF OffsetY= 0
DXF ScaleX= 0
DXF ScaleY= 0

--- BEARCMPRN.p01 (plan) ---

Plan Title=Floodplain
Program Version=6.20
Short Identifier=Floodplain
Geom File=g01
Flow File=f01
Subcritical Flow
K Sum by GR= 0
Std Step Tol= 0.01
Critical Tol= 0.01
Num of Std Step Trials= 20
Max Error Tol= 0.3
Flow Tol Ratio= 0.001
Split Flow NTrial= 30
Split Flow Tol= 0.02
Split Flow Ratio= 0.02
Log Output Level= 0
Friction Slope Method= 1
Unsteady Friction Slope Method= 2
Unsteady Bridges Friction Slope Method= 1
Parabolic Critical Depth
Global Vel Dist= 0 , 0 , 0
Global Log Level= 0
CheckData=False
Encroach Param=-1 ,0,0, 0
Mapping Interval=1HOUR
Computation Time Step Use Courant=        0
Computation Time Step Use Time Series=    0
Computation Time Step Count To Double=0
Computation Time Step Max Doubling=0
Computation Time Step Max Halving=0
Computation Time Step Residence Courant=0
Run HTab= 0
Run UNet= 0
Run Sediment= 0
Run PostProcess= 0
Run WQNet= 0
Run RASMapper=-1
UNET Theta= 0
UNET Theta Warmup= 0
UNET ZTol= 0
UNET ZSATol= 0
UNET MxIter= 0
UNET Max Iter WO Improvement= 0
UNET MaxInSteps= 0
UNET DtIC= 0
UNET DtMin= 0
UNET MaxCRTS= 0
UNET WFStab= 0
UNET SFStab= 0
UNET WFX= 1
UNET SFX= 1
UNET Gravity=32.174
UNET 1D Methodology=Finite Difference
UNET DSS MLevel= 1
UNET Pardiso=0
UNET DZMax Abort= 0
UNET Use Existing IB Tables= 0
UNET Froude Reduction=False
UNET Froude Limit= 0
UNET Froude Power= 0
UNET D1 Cores= 0
UNET WindReference=Eulerian
UNET WindDragFormulation=Hsu (1988)
UNET D2 Coriolis=0
UNET D2 Cores= 0
UNET D2 Theta= 1
UNET D2 Theta Warmup= 1
UNET D2 Z Tol= 0.01
UNET D2 Volume Tol= 0.01
UNET D2 Max Iterations= 20
UNET D2 Equation= 0
UNET D2 RampUpFraction=0.1
UNET D2 TimeSlices= 1
UNET D2 Turbulence Formulation=Non-Conservative (original)
UNET D2 Eddy Viscosity=0.3
UNET D2 Transverse Eddy Viscosity=0.1
UNET D2 Smagorinsky Mixing=0
UNET D2 BCVolumeCheck=0
UNET D2 Cores=0
UNET D2 SolverType=PARDISO (Direct)
UNET D2 Minimum Iterations= 2147483647
UNET D2 Maximum Iterations= 2147483647
UNET D2 Restart Number= 10
UNET D2 Relaxation Coeff=1.3
UNET D2 SOR Precondition Iterations= 10
UNET D2 ILUT Maximum Fill= 8
UNET D2 ILUT Tolerance=1E-08
UNET D1D2 MaxIter= 0
UNET D1D2 ZTol=0.01
UNET D1D2 QTol=0.1
UNET D1D2 MinQTol=1
Write IC File= 0
Write IC File at Fixed DateTime=0
Write IC File at Sim End=0
Echo Input=False
Echo Parameters=False
Echo Output=False
Write Detailed= 0
HDF Write Warmup=0
HDF Write Time Slices=0
HDF Flush=0
HDF Compression= 1
HDF Chunk Size= 1
HDF Spatial Parts= 1
HDF Use Max Rows=0
HDF Fixed Rows= 1
Calibration Method= 0
Calibration Iterations= 20
Calibration Max Change=0.05
Calibration Tolerance=0.2
Calibration Maximum=1.5
Calibration Minimum=0.5
Calibration Optimization Method= 1
WQ AD Non Conservative
WQ ULTIMATE=-1
WQ Max Comp Step=1HOUR
WQ Output Interval=15MIN
WQ Output Selected Increments= 0
WQ Output face flow=0
WQ Output face velocity=0
WQ Output face area=0
WQ Output face dispersion=0
WQ Output cell volume=0
WQ Output cell surface area=0
WQ Output cell continuity=0
WQ Output cumulative cell continuity=0
WQ Output face conc=0
WQ Output face dconc_dx=0
WQ Output face courant=0
WQ Output face peclet=0
WQ Output face adv mass=0
WQ Output face disp mass=0
WQ Output cell mass=0
WQ Output cell source sink temp=0
WQ Output nsm pathways=0
WQ Output nsm derived pathways=0
WQ Create Restart=0
WQ Fixed Restart=0
WQ System Summary=0
WQ Write To DSS=0
Sorting and Armoring Iterations= 10
XS Update Threshold= 0.02
Bed Roughness Predictor= 0
Hydraulics Update Threshold= 0.02
Energy Slope Method= 1
Volume Change Method= 1
Sediment Retention Method= 0
Sediment TS Multiplier= 1
Warm Up Method= 0
XS Weighting Method= 0
Number of US Weighted Cross Sections= 1
Number of DS Weighted Cross Sections= 1
Upstream XS Weight=0
Main XS Weight=1
Downstream XS Weight=0
Number of DS XS's Weighted with US Boundary= 1
Upstream Boundary Weight= 1
Weight of XSs Associated with US Boundary= 0
Number of US XS's Weighted with DS Boundary= 1
Downstream Boundary Weight= 0.5
Weight of XSs Associated with DS Boundary= 0.5
Percentile Method= 0
Sediment Output Level= 3
Mass or Volume Output= 0
Output Increment Type= 1
Profile and TS Output Increment= 1
Transport Output Increment 1
XS Output Flag= 0
XS Output Increment= 10
Read HDF5 Sediment Hotstart= 0
Sediment Hotstart Type= 0
Write Gradation File= 0
Read Gradation Hotstart= 0
Write HDF5 File= 1
Write Binary Output= 1
Write DSS Sediment File= 0
DSS Sediment Output Type= 1
SV Curve= 0
Specific Gage Flag= 0
Subcell Erosion Methods= 0
Subcell Deposition Methods= 0
Advection Scheme= 1
Matrix Solver= 0
Implicit Weighting Factor= 1
Maximum Outer Loop Convergence Iterations= 5
Convergence Maximum Absolute= 0.001
Convergence RMSE= 0.0001
Grain Fractions Max Abs Error= 0.001
Max Subgrid Regions= 1
Max Subgrid Length Scale= 3.402823E+38
Initial Layer Thickness= 3.402823E+38
Min Layer Thickness= 3.402823E+38
Max Layer Thickness= 3.402823E+38
Number of Layers= 5

--- BEARCMPRN.f01 (steady flow) ---

Flow Title=Flow
Program Version=6.20
Number of Profiles= 1
Profile Names=P100yr
River Rch & RM=BEARCMPRN,Main            ,13393
     353
River Rch & RM=BEARCMPRN,Main            ,10398
     407
River Rch & RM=BEARCMPRN,Main            ,8837
     453
River Rch & RM=BEARCMPRN,Main            ,5334
     537
River Rch & RM=BEARCMPRN,Main            ,2797
     597
Boundary for River Rch & Prof#=BEARCMPRN,Main            , 1
Up Type= 0
Dn Type= 1
Dn Known WS=2225.61
DSS Import GetInterval= 0
DSS Import GetPeak= 0
DSS Import FillOption= 0

--- BEARCMPRN.g01 (geometry) ---

Geom Title=Geometry
Program Version=6.20

River Reach=BEARCMPRN       ,Main
Reach XY= 30
     2206889.098      627084.588     2206551.598      627513.755
     2206566.702      627813.234     2206291.381      627819.335
     2206205.418      628190.6652205470.39755598629289.491003844
     2205205.573       629886.542204536.40728536630307.065128536
      2204447.03      630661.382     2204510.224      630809.993
2204270.75772691630952.464453474     2204203.974      631524.229
     2203967.298      631605.174     2203987.293      632314.486
      2204203.96      632818.652     2204445.627      632993.131
     2204361.599      633381.543     2204140.766      633570.085
     2204136.413      634026.676     2203849.303      634227.847
     2203954.421      634618.022     2203709.396      634729.941
      2203719.02      635239.484     2203457.037      635432.835
     2203610.596      635751.9072203444.29753408635914.539260224
      2203443.27      636587.439       2203655.5      636967.144
     2203569.021      637168.894     2203748.392      637390.825

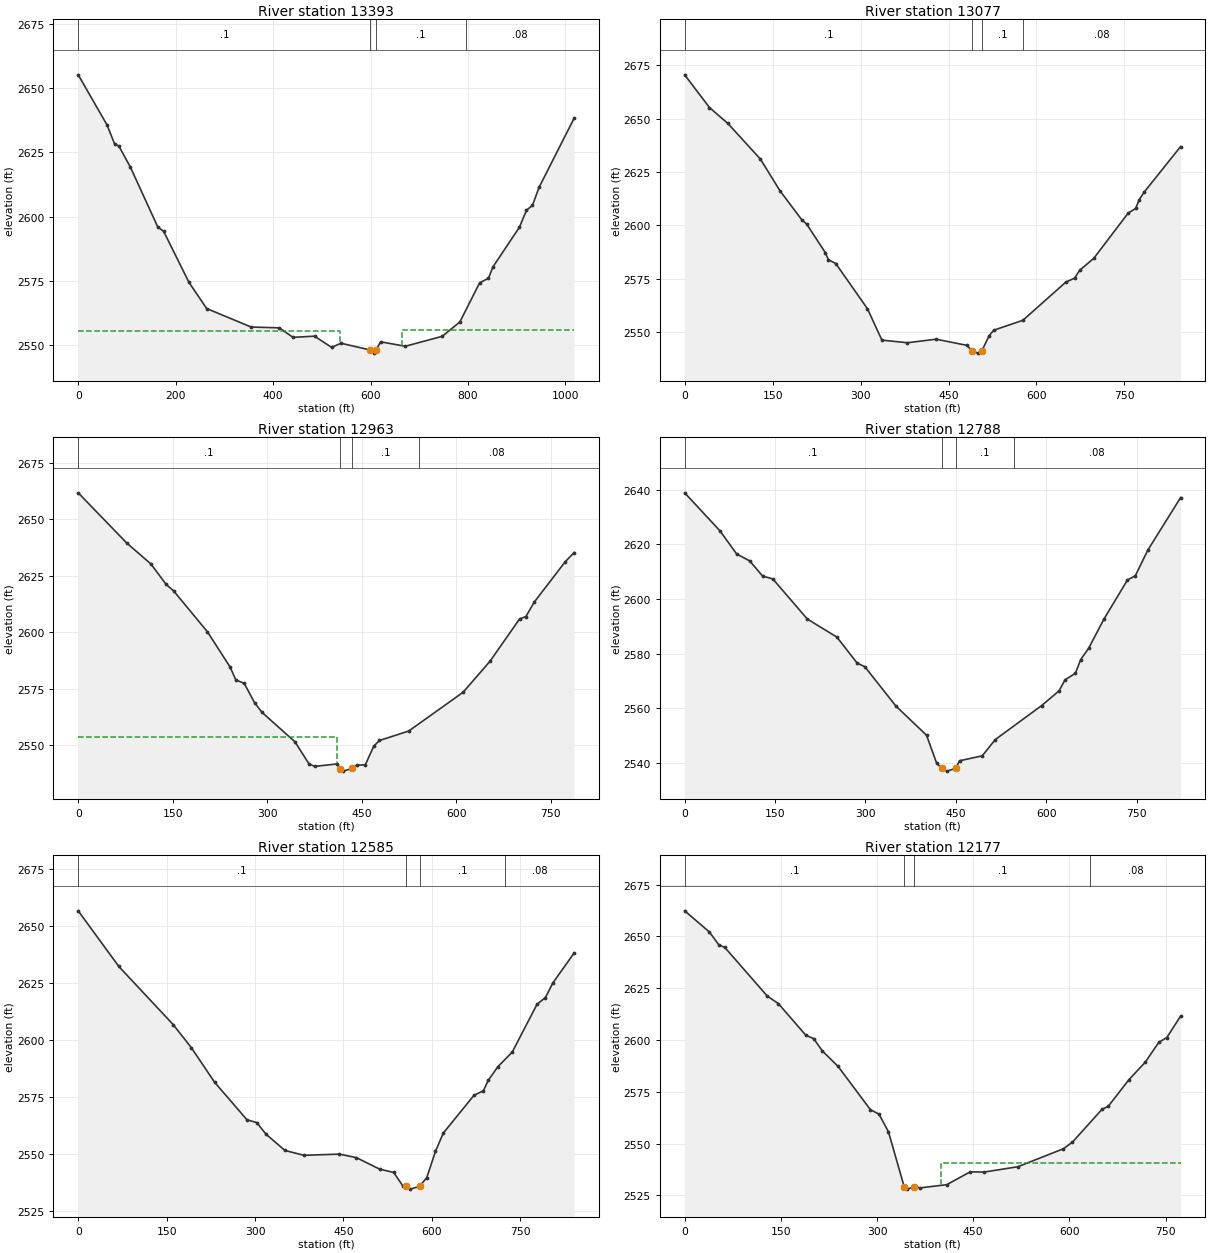
Type RM Length L Ch R = 1 ,13393   ,316.1,316.1,316.1
XS GIS Cut Line= 3
2206429.24371378626781.3892042762206695.03112927626799.719370862
2207044.61359201627464.842558392
#Sta/Elev= 30
       0  2655.3    59.1 2635.77    75.1 2628.14    83.1 2627.62   107.2 2619.24
   163.3 2595.95   175.3 2594.26   227.3 2574.34   263.6 2564.13   354.9 2556.91
   412.7 2556.59   440.8 2552.89     485 2553.34   520.1 2548.97   539.2 2550.59
  599.522547.935     607 2546.73   611.5 2547.94   620.5 2551.15   671.2 2549.41
   747.1 2553.29   783.2 2558.88   823.9 2574.19     842 2575.92     851 2580.33
   905.4 2595.84     920 2602.46   932.3 2604.42   945.9 2611.46  1017.8 2638.38
#Mann= 4 ,-1,0
       0      .1       0  599.52    .045       0   611.5      .1       0
  796.42     .08       0
#XS Ineff= 2 , 0
          536.55 2555.24  664.01         2555.61
Permanent Ineff=
       F       F
Bank Sta=599.52,611.5
XS Rating Curve= 0 ,0
Exp/Cntr(USF)=0,0
Exp/Cntr=0.3,0.1

Type RM Length L Ch R = 1 ,13077   ,114.1,114.1,114.1
XS GIS Cut Line= 4
2206315.33482143627083.8369529362206630.87554622627168.941297798
2206778.82617652 627391.52189205  2207004.025366627504.121486789
#Sta/Elev= 30
       0 2670.52    42.3 2655.19    73.6 2647.77   129.3    2631   162.4 2616.25
   199.7 2602.62     208 2600.64     240 2587.15   245.3 2583.84   257.7 2582.12
   311.8  2560.9   336.4 2546.22   379.9    2545   428.9 2546.66   480.8 2543.81
   490.4  2541.3     500 2540.13   506.8 2541.18   519.2 2548.25     527 2550.85
   576.9 2555.52     650 2573.37   664.9 2575.26   673.8 2578.96   697.7 2584.52
   756.6 2605.79   769.2  2607.9   775.2 2611.95   783.4 2615.46   845.9 2636.92
#Mann= 4 ,-1,0
       0      .1       0   490.4    .045       0   506.8      .1       0
  576.82     .08       0
Bank Sta=490.4,506.8
XS Rating Curve= 0 ,0
Exp/Cntr(USF)=0,0
Exp/Cntr=0.3,0.1

Type RM Length L Ch R = 1 ,12963   ,175.2,175.2,175.2
XS GIS Cut Line= 2
2206260.34432167627197.745845289 2206964.7464376 627548.63760564
#Sta/Elev= 30
       0 2661.66      77 2639.47   115.4 2630.21   139.6 2621.15   151.8 2618.19
   205.1 2600.21   241.1 2584.62     250 2579.01   263.5 2577.39   279.8  2568.9
   291.8 2564.57   343.9  2551.6   366.3 2541.81   375.2 2540.73   410.9 2541.81
   415.4 2539.71   420.4 2538.63     435 2539.81   442.2 2541.26   455.6 2541.41
     469 2549.68     478 2552.17   524.4 2556.34   610.9 2573.52   653.6 2587.25
   700.4 2605.91   710.4 2606.96   723.8 2613.41   772.9 2631.22     787 2635.28
#Mann= 4 ,-1,0
       0      .1       0   415.4    .045       0     435      .1       0
     540     .08       0
#XS Ineff= 2 , 0
          411.26 2553.93
Permanent Ineff=
       F       F
Bank Sta=415.4,435
XS Rating Curve= 0 ,0
Exp/Cntr(USF)=0,0
Exp/Cntr=0.3,0.1

Type RM Length L Ch R = 1 ,12788   ,202.3,202.3,202.3
XS GIS Cut Line= 4
 2206134.6517508627375.8103206912206488.20671263627503.954233747
2206653.29830888 627559.72772122  2206905.828045627662.546497992
#Sta/Elev= 30
       0  2638.8    58.5 2624.91    86.2 2616.44     108 2613.88   129.3 2608.36
   146.3 2607.29   203.6 2592.62   252.6 2586.02   286.4 2576.47   298.9 2575.21
   350.5 2560.81   401.4 2550.12   418.2 2539.88   426.7 2538.01   435.1    2537
   449.6 2537.99   456.2 2540.79   493.8  2542.6   515.4 2548.54   592.3 2560.97
   621.2 2566.35   631.2 2570.38   648.4 2572.79   657.1 2577.77   670.3 2581.91
   695.9 2592.67   734.8 2606.93   747.8 2608.44   768.5 2617.81     823 2637.08
#Mann= 4 ,-1,0
       0      .1       0   426.7    .045       0   449.6      .1       0
  546.06     .08       0
Bank Sta=426.7,449.6
XS Rating Curve= 0 ,0
Exp/Cntr(USF)=0,0
Exp/Cntr=0.3,0.1

Type RM Length L Ch R = 1 ,12585   ,408.8,408.8,408.8
XS GIS Cut Line= 4
2206049.54740594627581.3700459712206294.38605962627692.660343097
2206729.07286721627717.5369977492206845.60035479627789.548366477
#Sta/Elev= 30
       0 2656.64    68.8 2632.29   161.1  2606.8   191.8 2596.72   231.5 2581.49
   286.3 2565.08   302.8 2563.87   318.8 2558.72   350.7 2551.66   382.9 2549.52
     443 2550.05     472  2548.5   511.1 2543.49   535.2    2542   551.2 2535.92
  556.062535.985   563.2 2534.71   579.2 2535.96   591.3 2539.76     606  2551.2
   619.3 2559.27   671.4 2575.82   687.4 2577.81   695.4 2582.32   712.1 2588.41
   736.2 2594.72   778.5 2615.77   792.6 2618.63   805.1 2625.03   841.3  2638.2
#Mann= 4 ,-1,0
       0      .1       0  556.06    .045       0   579.2      .1       0
  724.34     .08       0
Bank Sta=556.06,579.2
XS Rating Curve= 0 ,0
Exp/Cntr(USF)=0,0
Exp/Cntr=0.3,0.1

Type RM Length L Ch R = 1 ,12177   ,202.8,202.8,202.8
XS GIS Cut Line= 3
2206016.81496561627604.9374030092206451.50177321627912.622342123
2206680.62885552627987.252306078
#Sta/Elev= 30
       0 2662.34    38.4 2652.18    53.1 2645.98    62.7 2644.65   128.8 2621.22
   146.1 2617.58   189.1 2602.26   201.2 2600.69   214.8 2594.71   239.3 2587.27
   289.5 2566.46   303.1  2564.2   317.8 2555.76   342.3 2529.26   346.9 2528.06
   358.4 2529.32     367 2528.65   408.9 2530.22   445.2 2536.39   467.4  2536.3
   519.7 2538.87   590.7 2547.54   604.8 2550.74   650.9 2566.57   660.5 2567.98
   693.1 2580.95   718.4 2589.32   739.4 2598.86     752 2601.21   773.5 2611.55
#Mann= 4 ,-1,0
       0      .1       0   342.3    .045       0   358.4      .1       0
  632.56     .08       0
#XS Ineff= 2 , 0
                          400.15         2540.44
Permanent Ineff=
       F       F
Bank Sta=342.3,358.4
XS Rating Curve= 0 ,0
Exp/Cntr(USF)=0,0
Exp/Cntr=0.3,0.1

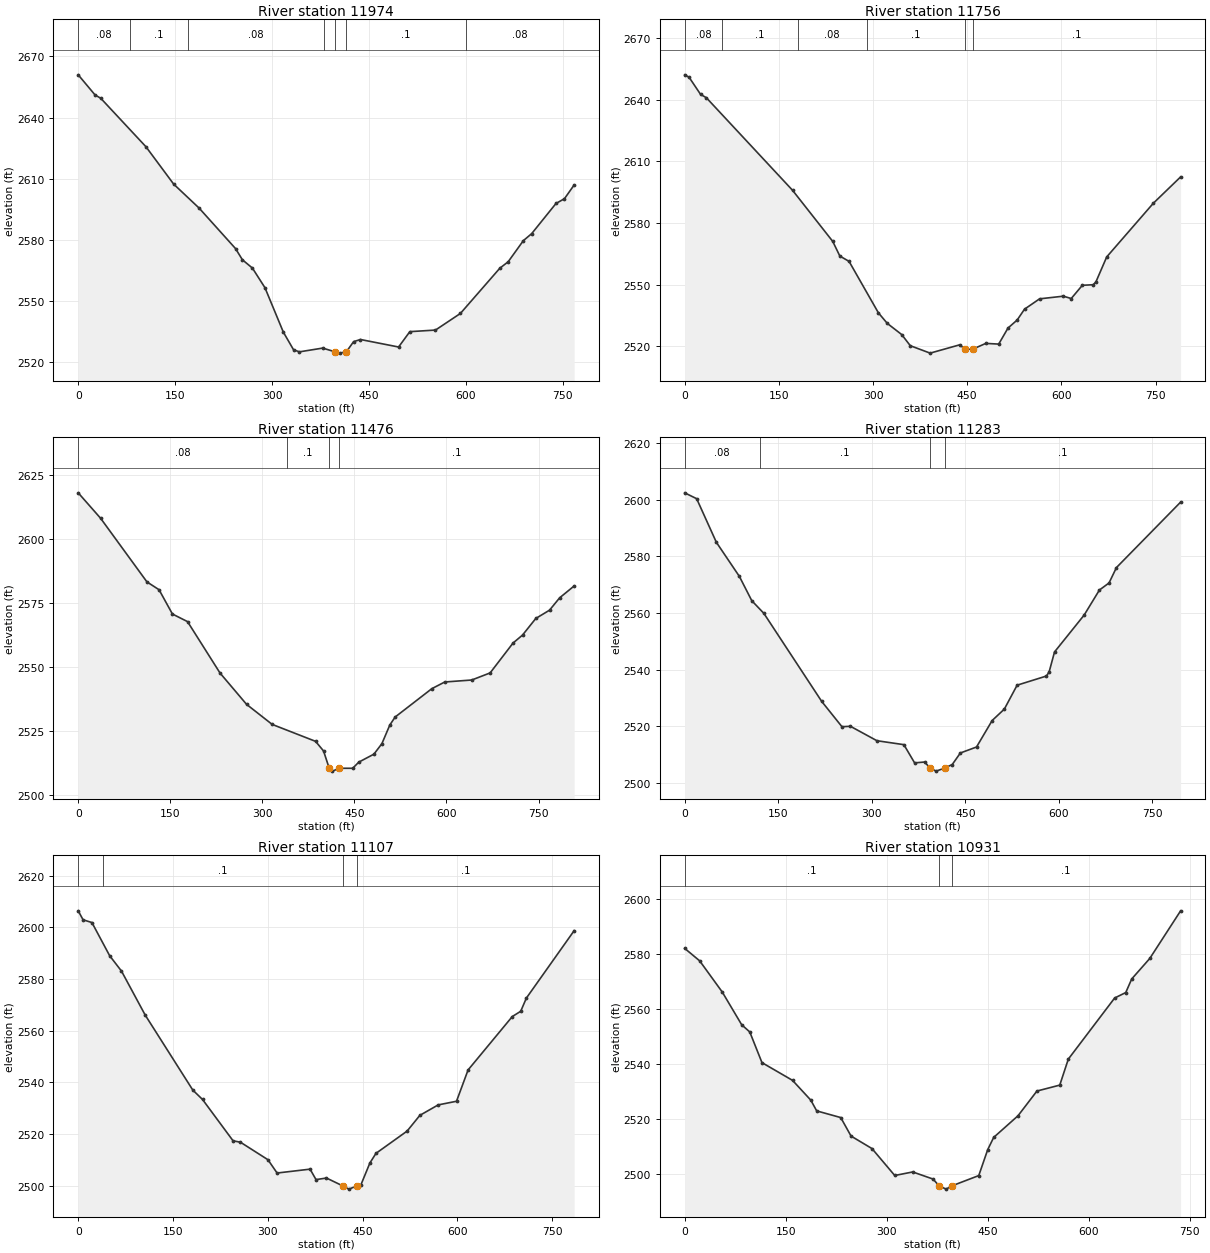
Type RM Length L Ch R = 1 ,11974   ,217.6,217.6,217.6
XS GIS Cut Line= 2
2205900.28747803627839.3016757812206605.99889157628141.749424441
#Sta/Elev= 30
       0 2660.96      26 2651.12    34.9 2649.46   104.9 2625.68   147.8 2607.36
   187.2  2595.6   243.6 2575.74   254.2 2570.25   269.7 2566.19   289.1 2556.56
   317.6 2534.76   333.4 2526.11   342.5 2525.11   378.5 2526.95  398.142525.069
   404.6 2524.48   415.1 2525.13   426.4 2530.12     437 2531.16     496 2527.48
   513.4 2535.01   553.1 2535.79   591.7 2543.94   652.7 2566.11   665.7  2569.3
   689.2 2579.66     702 2583.06   739.7 2597.88   752.8 2600.22   767.8 2606.95
#Mann= 7 ,-1,0
       0     .08       0      80      .1       0     170     .08       0
     380      .1       0  398.14    .045       0   415.1      .1       0
     600     .08       0
Bank Sta=398.14,415.1
XS Rating Curve= 0 ,0
Exp/Cntr(USF)=0,0
Exp/Cntr=0.3,0.1

Type RM Length L Ch R = 1 ,11756   ,280.6,280.6,280.6
XS GIS Cut Line= 3
2205806.01804987627979.3965203982206350.68585698628281.844269059
2206505.18297535628344.690554495
#Sta/Elev= 30
       0 2652.11       7 2650.94    25.3  2642.6    34.5 2640.97   171.8 2595.92
   235.8 2571.05   247.1 2563.93   261.8 2561.33   308.5  2536.3   322.7 2531.15
   345.6 2525.73   359.3  2520.3   390.9 2516.69   438.3 2520.76  445.862518.626
   458.9 2518.64   479.5 2521.42   500.1 2521.09   514.9 2528.89   529.5  2532.8
   541.2 2538.07   565.2 2543.11     603  2544.4   615.6 2543.26   633.3  2549.7
   650.5 2549.97   654.8 2551.27   672.1  2563.5   746.4 2589.64   789.8 2602.44
#Mann= 6 ,-1,0
       0     .08       0      60      .1       0     180     .08       0
     290      .1       0  445.86    .045       0   458.9      .1       0
Bank Sta=445.86,458.9
XS Rating Curve= 0 ,0
Exp/Cntr(USF)=0,0
Exp/Cntr=0.3,0.1

Type RM Length L Ch R = 1 ,11476   ,193,193,193
XS GIS Cut Line= 2
2205642.35584822628234.7095549822206389.96478538628541.085196482
#Sta/Elev= 30
       0  2618.1    36.5 2608.16     112 2583.32   131.7 2580.27   153.5 2570.78
   178.1 2567.82   231.1 2547.73   274.3 2535.52     316 2527.69   386.7 2521.08
   399.7 2517.32     409 2510.52   414.2 2509.45   425.6 2510.57   447.2 2510.56
   457.1 2512.96   481.8 2516.08   494.8 2520.19   507.7 2527.46   516.4 2530.58
   576.1 2541.64   597.2 2544.25   641.1 2545.02   671.1 2547.79   708.5 2559.47
   723.9 2562.57   745.5 2569.05   767.9 2572.29   784.4 2577.12     808 2581.74
#Mann= 4 ,-1,0
       0     .08       0     340      .1       0     409    .045       0
   425.6      .1       0
Bank Sta=409,425.6
XS Rating Curve= 0 ,0
Exp/Cntr(USF)=0,0
Exp/Cntr=0.3,0.1

Type RM Length L Ch R = 1 ,11283   ,176,176,176
XS GIS Cut Line= 2
2205566.41658665628412.7740303842206303.55114291628711.293886204
#Sta/Elev= 30
       0 2602.41    19.2 2600.34    50.8 2584.94    87.7 2572.89   107.6 2564.31
     127 2559.83   219.7 2528.74   252.2 2519.79   265.8 2519.94   308.3 2514.84
   351.5 2513.45   368.7 2507.02   384.7 2507.31  393.812505.164   403.2  2504.1
   416.82505.157   429.1 2506.44   442.1 2510.51     468 2512.62   493.1 2521.98
   512.6 2526.01   533.1 2534.46   580.2  2537.7   584.5  2539.2   593.1  2546.2
   640.6 2559.23   665.1 2568.08   680.5 2570.57   692.4 2576.01   795.3 2599.13
#Mann= 4 ,-1,0
       0     .08       0     120      .1       0  393.81    .045       0
   416.8      .1       0
Bank Sta=393.81,416.8
XS Rating Curve= 0 ,0
Exp/Cntr(USF)=0,0
Exp/Cntr=0.3,0.1

Type RM Length L Ch R = 1 ,11107   ,175.5,175.5,175.5
XS GIS Cut Line= 4
2205537.61203916628438.9599826492205768.04841909628579.054827266
2205950.04078733628865.7910045682206108.46579853628941.730266136
#Sta/Elev= 30
       0 2606.42     7.7 2602.95    21.7 2601.89    49.8 2589.04    68.5  2583.1
     106  2566.1   181.4 2537.06   196.8 2533.42   245.1 2517.44   256.8 2516.89
   300.3 2510.12   314.8 2504.97     367 2506.47   376.4 2502.43     393 2503.03
   418.8 2499.99   428.5 2498.74   441.6 2500.03   447.5 2500.42   461.7 2508.86
   471.3 2512.58   520.6  2521.2   540.8 2527.29   569.8 2531.33   598.8 2532.74
   617.1 2544.85   687.1 2565.52   700.4 2567.55   709.4 2572.67     785 2598.75
#Mann= 4 ,-1,0
       0     .08       0      40      .1       0   418.8    .045       0
   441.6      .1       0
Bank Sta=418.8,441.6
XS Rating Curve= 0 ,0
Exp/Cntr(USF)=0,0
Exp/Cntr=0.3,0.1

Type RM Length L Ch R = 1 ,10931   ,181.2,181.2,181.2
XS GIS Cut Line= 2
2205400.13578977628678.5614458732206061.33108446629003.267253959
#Sta/Elev= 30
       0 2582.13    22.3 2577.57    55.8 2566.22    84.7 2554.28    96.7 2551.66
   114.8 2540.48   160.2 2534.02   187.3 2526.82   196.1 2522.89   231.8 2520.46
   247.1 2513.72   278.2 2509.16     312 2499.35   338.7 2500.64   368.9 2498.05
     378 2495.54   388.4 2494.38   396.5 2495.53   436.8 2499.32   450.1 2508.78
     459 2513.24   495.1 2521.12   523.2 2530.13   557.1 2532.29   569.8 2541.76
   638.6 2564.03   655.1 2566.02     664 2570.99   690.8 2578.45   736.6 2595.81
#Mann= 3 ,-1,0
       0      .1       0     378    .045       0   396.5      .1       0
Bank Sta=378,396.5
XS Rating Curve= 0 ,0
Exp/Cntr(USF)=0,0
Exp/Cntr=0.3,0.1

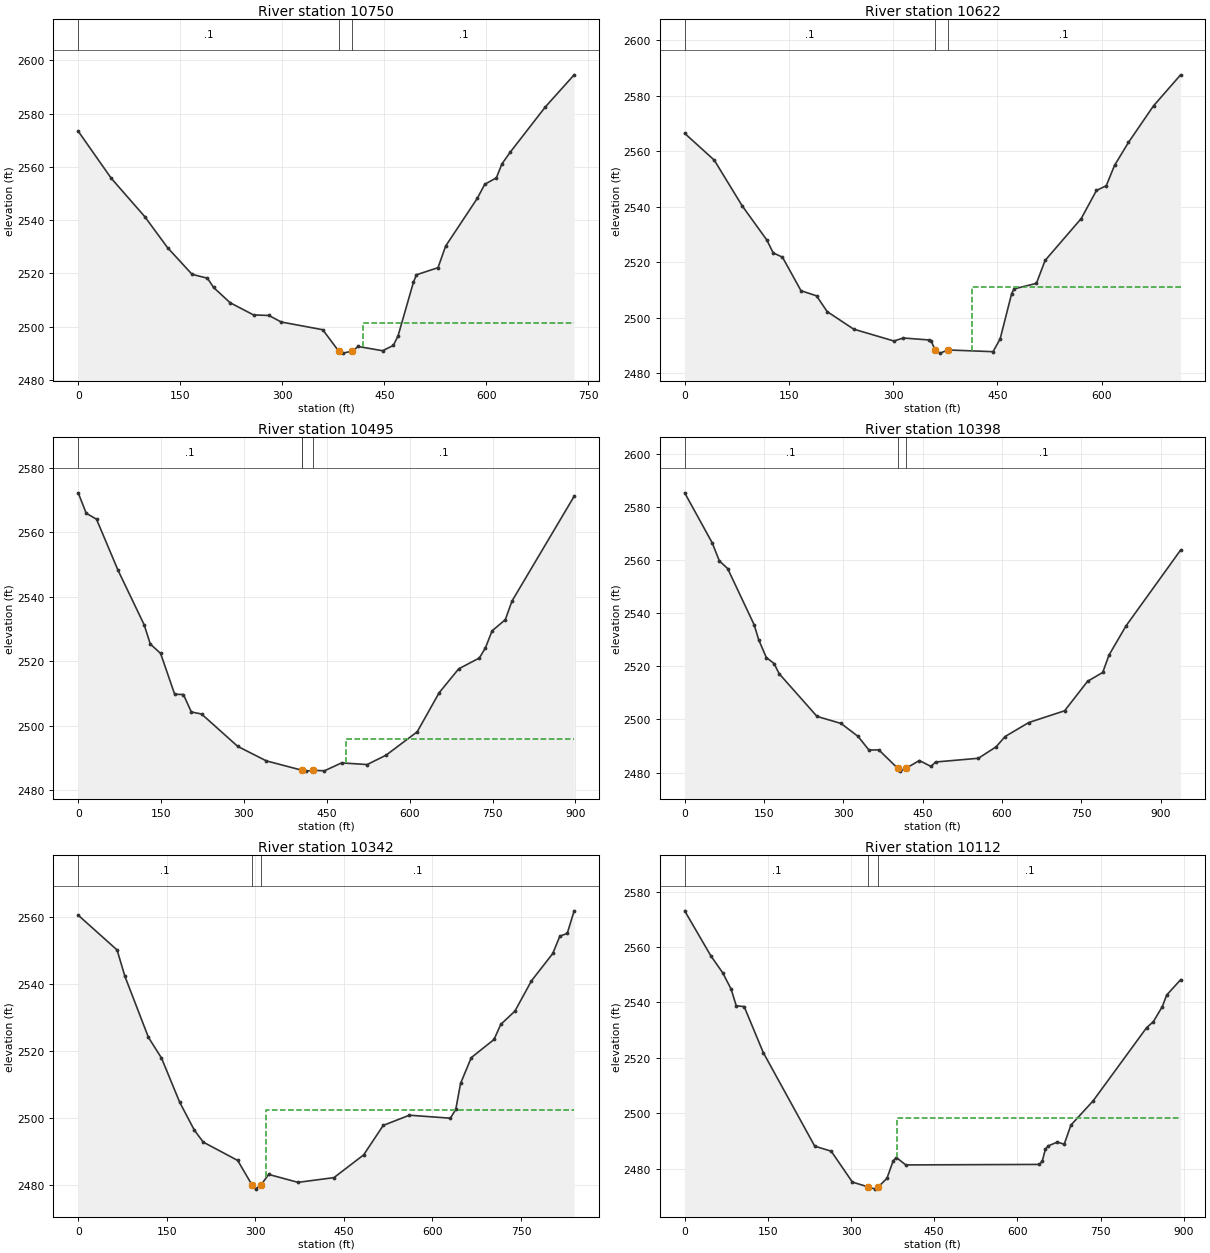
Type RM Length L Ch R = 1 ,10750   ,128.1,128.1,128.1
XS GIS Cut Line= 3
2205335.98020672628835.6771594632205819.11102601629089.680896433
2206002.41269186 629092.29949166
#Sta/Elev= 30
       0 2573.38    48.6 2555.69    97.8 2541.32   131.3 2529.68   167.4 2519.64
     190 2518.19   199.1  2514.7   223.4 2508.97   257.8  2504.4   280.4  2504.2
   298.5 2501.75   359.6 2498.84     3832490.814   389.3 2490.06   403.22490.825
   411.5 2492.56   447.6 2490.96   463.3 2492.95   470.2 2496.48   492.9 2516.69
   497.3 2519.47     529 2522.14   540.3 2530.27   586.9 2548.22   597.7 2553.43
   614.9 2555.89   622.9 2561.06   634.9  2565.4   686.9 2582.51   729.2 2594.54
#Mann= 3 ,-1,0
       0      .1       0     383    .045       0   403.2      .1       0
#XS Ineff= 2 , 0
                          418.77         2501.52
Permanent Ineff=
       F       F
Bank Sta=383,403.2
XS Rating Curve= 0 ,0
Exp/Cntr(USF)=0,0
Exp/Cntr=0.3,0.1

Type RM Length L Ch R = 1 ,10622   ,127.2,127.2,127.2
XS GIS Cut Line= 3
2205285.93594239628965.0066681492205744.19010702629190.205857628
2205947.13123708629192.824452854
#Sta/Elev= 30
       0 2566.44    42.6 2556.76    82.7 2540.33   118.3 2527.96   127.3 2523.37
   140.7 2521.81   167.4 2509.72   189.7 2507.89     205 2502.21   243.2 2495.88
   301.1 2491.61   314.5 2492.69   351.4 2491.99   354.6 2491.71   360.4 2488.27
     368 2487.24   378.3 2488.39   443.7 2487.76   453.9 2492.36   470.5 2508.72
     474 2510.38   506.1 2512.38   518.6 2520.63   570.6 2535.74   592.5 2545.84
   606.6 2547.56   618.6 2554.92   638.6 2563.17   674.6 2576.34   713.6 2587.51
#Mann= 3 ,-1,0
       0      .1       0   360.4    .045       0   378.3      .1       0
#XS Ineff= 2 , 0
                          413.84         2511.03
Permanent Ineff=
       F       F
Bank Sta=360.4,378.3
XS Rating Curve= 0 ,0
Exp/Cntr(USF)=0,0
Exp/Cntr=0.3,0.1

Type RM Length L Ch R = 1 ,10495   ,96.5,96.5,96.5
BEGIN DESCRIPTION:
Structure XS 3
END DESCRIPTION:
XS GIS Cut Line= 6
2205267.68034269 628972.650672722205483.35765743  629099.5390126
2205502.21154306629187.9166014942205628.29690322629302.218283131
2205713.13938855629499.0057144022205884.62137805629492.049035895
#Sta/Elev= 30
       0 2572.27    14.5 2565.93    33.1 2564.09      72 2548.25   119.4 2531.28
   130.5 2525.31   149.1 2522.41   174.6 2509.72   190.4 2509.63   204.8 2504.21
   223.3 2503.58   288.7 2493.53   340.6 2489.02   405.3  2486.1405.31392486.099
   412.4 2485.84   424.9  2486.1   445.6 2485.94   476.8  2488.4     523 2487.88
   557.2 2490.79   613.6 2498.05   653.3 2510.18   688.7 2517.61   726.1 2520.97
   737.1 2524.12   749.1  2529.4   773.1 2532.88   785.1 2538.63   897.7  2571.2
#Mann= 4 ,-1,0
       0      .1       0   405.3    .045       0405.3139    .045       0
   424.9      .1       0
#XS Ineff= 2 , 0
                          485.21         2495.93
Permanent Ineff=
       F       F
Bank Sta=405.3139,424.9
XS Rating Curve= 0 ,0
Exp/Cntr(USF)=0,0
Exp/Cntr=0.3,0.1

Type RM Length L Ch R = 1 ,10398   ,56,56,56
BEGIN DESCRIPTION:
Structure XS 2
END DESCRIPTION:
XS GIS Cut Line= 6
2205211.61088852629006.5391207512205427.28820326629133.427460631
2205463.81760667629274.8316028622205592.32007856629344.566785691
2205679.27757752629532.8941624332205863.44964881629526.994990742
#Sta/Elev= 30
       0 2585.24      52 2566.44    65.6 2559.62    81.2 2556.76   131.4 2535.58
   139.9 2529.97   154.3 2523.28   168.9 2521.03   178.7 2517.18   250.2 2501.12
   295.6 2498.48   327.7 2493.62   348.4 2488.47     367 2488.54   402.4 2481.68
   407.8 2480.54   418.5 2481.62   443.7 2484.53   465.8 2482.29   474.2 2483.97
   555.3 2485.38   588.8 2489.69   605.7 2493.55   650.5 2498.82   718.3 2503.25
   761.7 2514.34   790.3 2517.66   802.3 2524.24   834.3 2535.16   937.6 2563.72
#Mann= 3 ,-1,0
       0      .1       0   402.4    .045       0   418.5      .1       0
Bank Sta=402.4,418.5
XS Rating Curve= 0 ,0
Exp/Cntr(USF)=0,0
Exp/Cntr=0.3,0.1

Type RM Length L Ch R = 1 ,10342   ,229.7,229.7,229.7
BEGIN DESCRIPTION:
Structure XS 1
END DESCRIPTION:
XS GIS Cut Line= 4
2205176.67468502629205.0474173172205592.63853675629401.834848588
2205668.05407927629564.449612153 2205868.3766141 629556.20103719
#Sta/Elev= 30
       0 2560.53    65.8 2550.17    79.1  2542.3   118.9 2524.12     141 2517.96
     172 2504.72   196.7 2496.44   211.8 2492.88   270.1 2487.42   294.1 2480.18
   300.3 2478.87  309.962480.202   322.5 2483.26   372.2 2480.89   433.1  2482.3
   483.4 2489.08   516.6 2497.87   560.9 2500.91   630.2 2500.01   639.4 2502.61
   647.5 2510.37   665.7 2518.07   704.2 2523.48   715.6 2527.97   739.6 2531.94
   767.6 2540.97   803.7 2549.11   815.7 2554.28   828.2  2555.1   839.9 2561.83
#Mann= 3 ,-1,0
       0      .1       0   294.1    .045       0  309.96      .1       0
#XS Ineff= 2 , 0
                          318.76         2502.43
Permanent Ineff=
       F       F
Bank Sta=294.1,309.96
XS Rating Curve= 0 ,0
Exp/Cntr(USF)=0,0
Exp/Cntr=0.3,0.1

Type RM Length L Ch R = 1 ,10112   ,168.6,168.6,168.6
XS GIS Cut Line= 4
2205084.46413521629380.0831070522205301.80753901629466.496749526
2205623.89475187629763.7073077342205845.16604851629741.449248308
#Sta/Elev= 30
       0 2573.08      47  2556.9    68.6  2550.7    83.8 2544.81      93 2538.79
   107.3 2538.51   141.7 2521.92   234.6  2488.1   264.3 2486.29   302.4 2475.15
   330.9 2473.39     344 2472.59  349.062473.375   364.8 2476.48   376.2 2482.87
   381.8 2484.01   398.8 2481.33   639.9 2481.51   645.1  2482.8   650.7 2487.08
   656.2 2488.24   672.4  2489.6   684.5 2488.78   696.6  2495.7   736.8 2504.49
   833.2 2530.91   845.3 2533.05   861.4 2538.47   869.4 2542.68   894.5 2548.21
#Mann= 3 ,-1,0
       0      .1       0   330.9    .045       0  349.06      .1       0
#XS Ineff= 2 , 0
                          382.51         2498.31
Permanent Ineff=
       F       F
Bank Sta=330.9,349.06
XS Rating Curve= 0 ,0
Exp/Cntr(USF)=0,0
Exp/Cntr=0.3,0.1

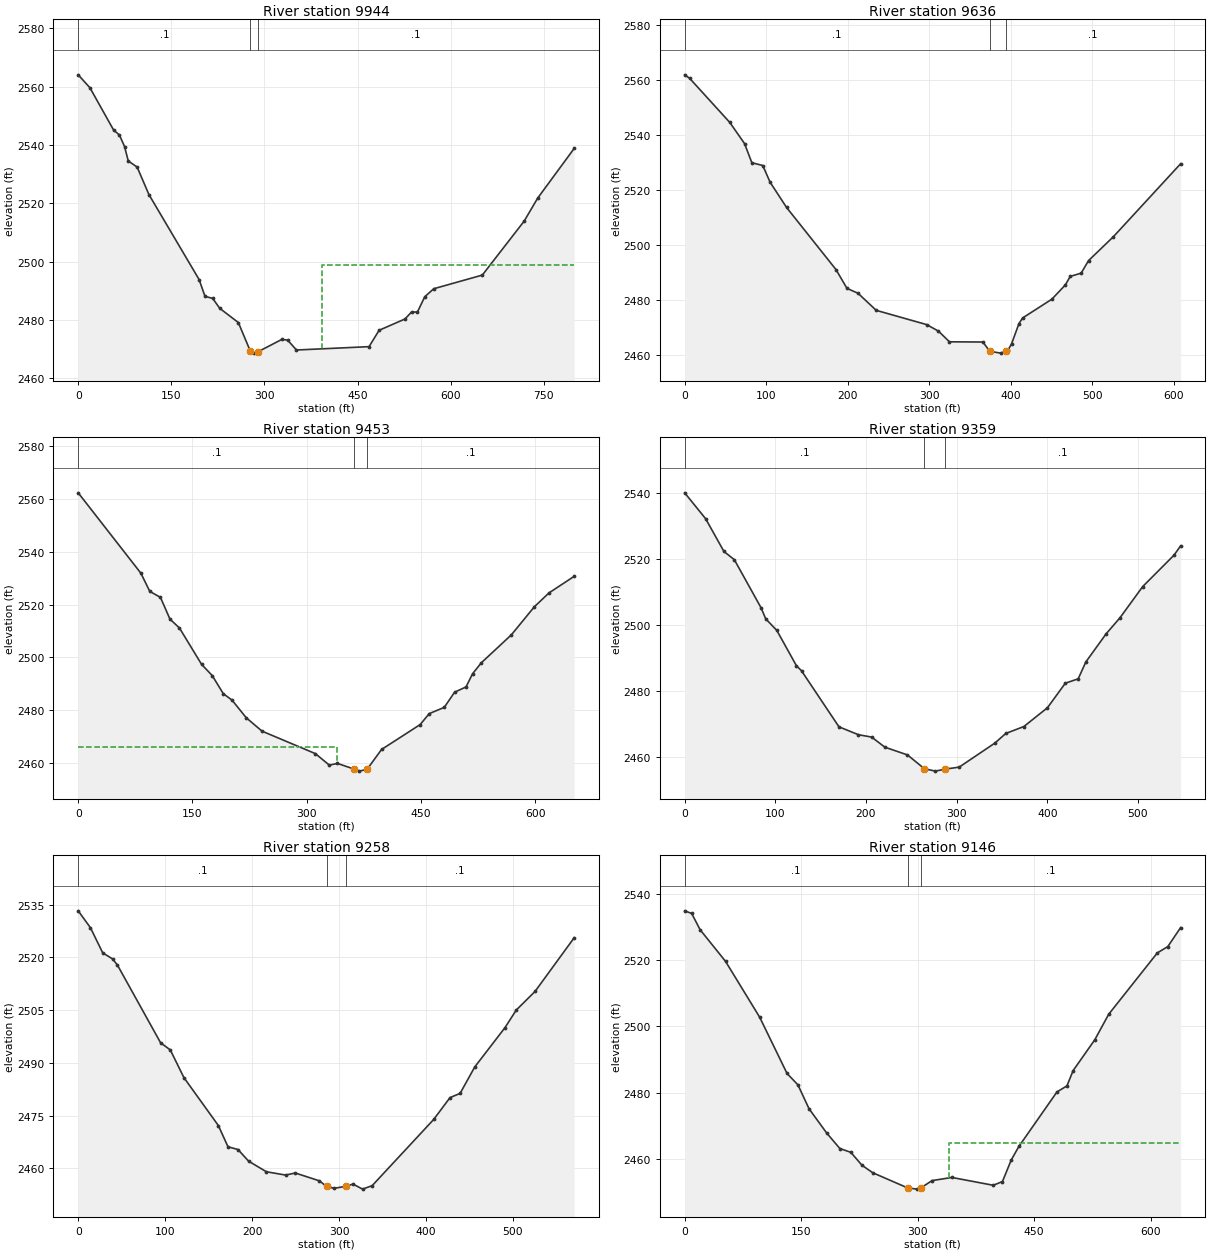
Type RM Length L Ch R = 1 ,9944    ,308.1,308.1,308.1
XS GIS Cut Line= 3
 2205028.2952676629509.9654302862205579.50956278629863.475785863
2205612.24200311 630003.57063048
#Sta/Elev= 30
       0 2564.03    18.9 2559.59    56.9 2545.14    66.4 2543.39    74.6 2539.46
    80.6 2534.51    94.9 2532.41   113.9 2522.98   194.7 2493.86   204.2 2488.08
   216.5 2487.42   227.9    2484   257.9 2479.12   277.3 2469.26   283.1 2468.64
   289.7 2469.12   327.7 2473.32   337.2 2473.12   351.5 2469.71   468.4 2470.86
   484.6 2476.47   526.3 2480.35   536.8 2482.73   546.3 2482.73   558.1 2487.96
   572.6 2490.71   650.8 2495.39   718.2 2513.89     740 2521.78   798.7 2538.79
#Mann= 3 ,-1,0
       0      .1       0   277.3    .045       0   289.7      .1       0
#XS Ineff= 2 , 0
                          391.99         2498.94
Permanent Ineff=
       F       F
Bank Sta=277.3,289.7
XS Rating Curve= 0 ,0
Exp/Cntr(USF)=0,0
Exp/Cntr=0.3,0.1

Type RM Length L Ch R = 1 ,9636    ,182.8,182.8,182.8
XS GIS Cut Line= 2
2204969.37687501 629555.79084675 2205245.6386714630097.840058635
#Sta/Elev= 30
       0 2561.84       6  2560.6    55.4 2544.54    73.4 2536.89    82.4 2529.94
    95.8 2528.92   104.8 2522.85     125 2513.69   185.6 2491.16   199.1 2484.33
   212.6 2482.56     235 2476.35   296.9 2471.17   311.3 2468.81   324.8 2464.93
   365.9 2464.85   374.2 2461.48   387.7 2460.82   393.8 2461.57   396.6 2461.89
   401.1 2464.26   410.1 2471.56   414.6 2473.59   450.5 2480.41     467 2485.58
     473 2488.67   486.4 2489.85   495.4 2494.39   525.9 2503.07   608.4 2529.56
#Mann= 3 ,-1,0
       0      .1       0   374.2    .045       0   393.8      .1       0
Bank Sta=374.2,393.8
XS Rating Curve= 0 ,0
Exp/Cntr(USF)=0,0
Exp/Cntr=0.3,0.1

Type RM Length L Ch R = 1 ,9453    ,93.6,93.6,93.6
XS GIS Cut Line= 4
2204803.09607813629657.916060583 2204939.2630299629821.578262239
2204985.08844637630000.9520352542205190.64817165630148.902665551
#Sta/Elev= 30
       0 2562.31    82.3 2531.87      94 2524.98     108 2522.71   120.5 2514.47
     133  2511.1   162.1  2497.3     176  2493.1   190.5 2486.25     202 2483.79
   220.7 2477.11   241.4 2472.04   311.6 2463.51   329.7 2459.18   340.5 2459.81
  362.772457.631   369.4  2456.9   379.42457.606   398.4 2465.11   449.1 2474.54
     461 2478.69   480.7 2481.04   494.3  2486.8   509.3 2488.79   517.9 2493.78
   529.4 2497.94   568.9 2508.53     599 2519.14   618.2 2524.39   651.3 2530.68
#Mann= 3 ,-1,0
       0      .1       0  362.77    .045       0   379.4      .1       0
#XS Ineff= 2 , 0
          340.44 2466.13
Permanent Ineff=
       F       F
Bank Sta=362.77,379.4
XS Rating Curve= 0 ,0
Exp/Cntr(USF)=0,0
Exp/Cntr=0.3,0.1

Type RM Length L Ch R = 1 ,9359    ,101.1,101.1,101.1
XS GIS Cut Line= 3
2204722.08178065629786.4682748432204933.58314386630060.245039444
2205093.38417384630182.445827077
#Sta/Elev= 30
       0  2540.2    23.1 2532.34    43.3 2522.39    54.8 2519.88    84.3 2505.26
    89.4 2501.92   101.6 2498.42   123.2 2487.71   128.9 2486.13   170.2 2469.11
   191.6 2466.72   206.3 2465.99   220.8 2462.93   245.8 2460.57   264.32456.408
   276.4 2455.65   287.52456.266   302.8 2456.86   342.1 2464.15   354.2 2467.09
   374.2  2469.2   400.2 2474.91   419.9 2482.36   434.1 2483.69   442.6 2488.84
     465 2497.39   480.1  2502.2   505.3 2511.73   539.7 2521.23   547.1 2524.08
#Mann= 3 ,-1,0
       0      .1       0   264.3    .045       0   287.5      .1       0
Bank Sta=264.3,287.5
XS Rating Curve= 0 ,0
Exp/Cntr(USF)=0,0
Exp/Cntr=0.3,0.1

Type RM Length L Ch R = 1 ,9258    ,112,112,112
XS GIS Cut Line= 3
2204616.83835738629864.5958560412204864.25769703630123.695448407
2205031.69353806630254.091833615
#Sta/Elev= 30
       0 2533.28    14.1 2528.46    28.2 2521.32    39.5  2519.6    45.1 2517.86
    94.8 2495.72   105.9 2493.71   121.6 2485.82   161.2 2472.19   172.3 2466.14
   183.8 2465.36     196 2462.05   216.5 2459.03   238.6 2458.09   249.7 2458.68
   277.3 2456.46   285.7 2454.86   294.4 2454.32   308.3 2454.91   316.1 2455.53
   327.1 2454.09   338.2 2455.09   408.9 2473.91   427.7 2480.13   439.3 2481.33
   456.2 2488.87   490.9 2500.03   503.9 2505.04   525.5 2510.34   570.5 2525.61
#Mann= 3 ,-1,0
       0      .1       0   285.7    .045       0   308.3      .1       0
Bank Sta=285.7,308.3
XS Rating Curve= 0 ,0
Exp/Cntr(USF)=0,0
Exp/Cntr=0.3,0.1

Type RM Length L Ch R = 1 ,9146    ,131.9,131.9,131.9
XS GIS Cut Line= 3
2204520.39558497629910.6191909682204807.01838072630217.760890762
2205002.97424186630314.435018255
#Sta/Elev= 30
       0 2534.83       9 2534.04    19.9 2529.12    52.6 2519.59    96.5 2502.77
   131.8 2485.77   145.8 2482.34   160.1 2475.14   182.8 2467.82   199.8 2463.13
   213.9 2461.99   228.3 2458.08   242.2 2455.82     287 2451.26   298.7 2450.88
   304.5 2451.31   318.6 2453.46   344.1  2454.4   397.4 2452.04   409.2 2453.18
   420.5 2459.67   430.3 2463.75   479.4 2480.21   492.2 2482.01   500.2 2486.64
   528.1 2495.94     546 2503.63   608.6 2522.14   622.1 2524.04   638.6 2529.78
#Mann= 3 ,-1,0
       0      .1       0     287    .045       0   304.5      .1       0
#XS Ineff= 2 , 0
                          340.44          2464.8
Permanent Ineff=
       F       F
Bank Sta=287,304.5
XS Rating Curve= 0 ,0
Exp/Cntr(USF)=0,0
Exp/Cntr=0.3,0.1

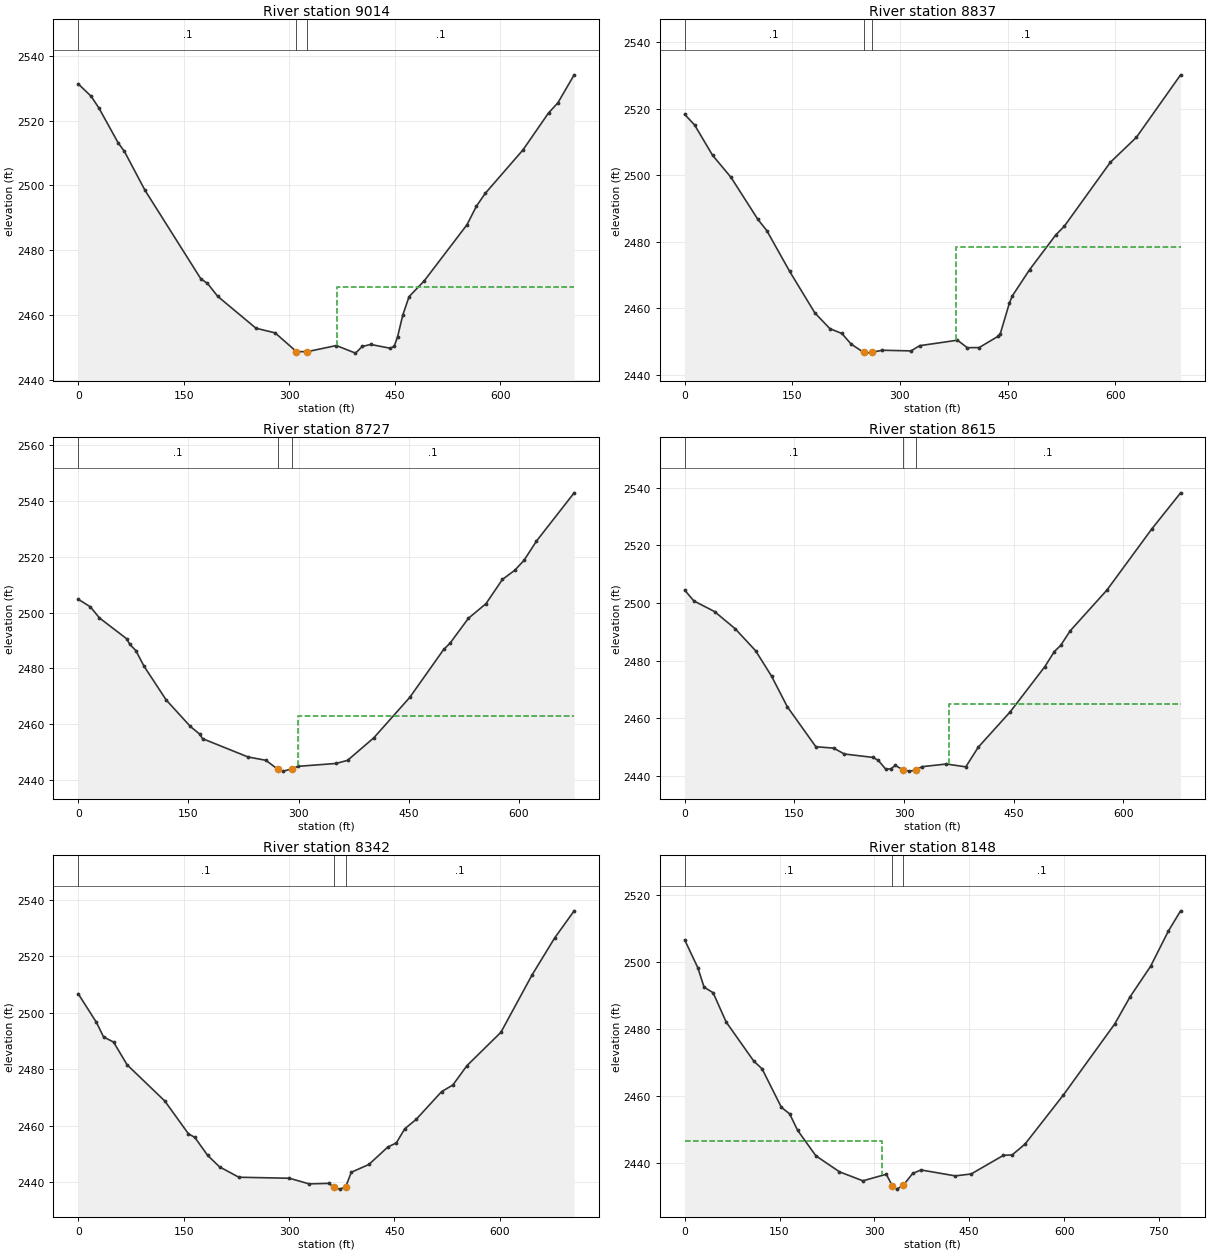
Type RM Length L Ch R = 1 ,9014    ,177.2,177.2,177.2
XS GIS Cut Line= 3
2204406.37890131630012.7357137732204754.65206643630333.513629019
 2204978.5419583630391.122724002
#Sta/Elev= 30
       0 2531.29    18.4 2527.48    29.6 2523.78    56.8 2513.11    65.6  2510.5
      95 2498.47   174.3 2471.21   183.7 2469.82   198.2 2465.84   252.6 2456.01
   279.8 2454.58   310.1 2448.81   325.4 2448.79   366.8 2450.68     394 2448.34
   403.6 2450.39   415.7 2451.01   443.2 2449.85   448.9  2450.4   453.8 2453.37
   461.2 2460.07   470.1 2465.74   491.6 2470.59   552.4 2487.89   565.9 2493.64
   578.3 2497.54     632 2510.96   668.3 2522.33   681.6 2525.46   704.7 2534.08
#Mann= 3 ,-1,0
       0      .1       0   310.1    .045       0   325.4      .1       0
#XS Ineff= 2 , 0
                          367.21         2468.76
Permanent Ineff=
       F       F
Bank Sta=310.1,325.4
XS Rating Curve= 0 ,0
Exp/Cntr(USF)=0,0
Exp/Cntr=0.3,0.1

Type RM Length L Ch R = 1 ,8837    ,109.8,109.8,109.8
XS GIS Cut Line= 5
 2204286.9837901630285.6540131722204501.77251608630352.568343392
2204650.76585644630353.3023240062204714.90616562630388.560281796
2204957.59319649630413.380783428
#Sta/Elev= 30
       0 2518.28    13.8  2515.1    38.9 2505.96    64.5 2499.35   101.8 2486.75
   114.4 2483.32   146.3 2471.03   181.4 2458.55   202.3 2453.81   219.1 2452.35
   231.9 2449.17249.45012446.654   251.4 2446.44260.79862446.687   275.4 2447.31
   315.4 2447.11   327.4 2448.68   380.1 2450.33   393.8 2448.08   410.3 2448.11
   436.8 2451.51   439.7 2452.21   452.5 2461.49   456.5 2463.63   480.6 2471.54
   516.8 2481.92   528.9 2484.59   593.2 2503.87   629.4 2511.35   691.1 2530.18
#Mann= 3 ,-1,0
       0      .1       0249.4501    .045       0260.7986      .1       0
#XS Ineff= 2 , 0
                          378.69         2478.26
Permanent Ineff=
       F       F
Bank Sta=249.4501,260.7986
XS Rating Curve= 0 ,0
Exp/Cntr(USF)=0,0
Exp/Cntr=0.3,0.1

Type RM Length L Ch R = 1 ,8727    ,112.4,112.4,112.4
XS GIS Cut Line= 5
2204288.21424118630400.3230195892204520.87657275630459.598922861
2204614.03757154630462.4553963872204679.91255958630514.555554773
2204924.92551142630594.321256176
#Sta/Elev= 30
       0 2504.77    16.5 2502.07    28.9 2498.08      66 2490.61    70.1 2488.66
    78.4  2486.4    89.5 2480.83   119.7 2468.72   152.7 2459.21   165.1 2456.54
   169.2 2454.86   231.1  2448.3   255.4 2447.11   271.4 2443.95   279.4 2443.23
290.33262444.012   299.4 2444.95     351 2445.98   366.6 2447.09   402.3 2455.15
   451.2 2469.61   497.5 2486.82   505.9 2488.97   531.1 2497.95     555 2503.19
   577.4 2511.87   594.1 2515.13   606.7 2518.67   623.7 2525.59     675 2542.87
#Mann= 3 ,-1,0
       0      .1       0   271.4    .045       0290.3326      .1       0
#XS Ineff= 2 , 0
                          299.64         2463.11
Permanent Ineff=
       F       F
Bank Sta=271.4,290.3326
XS Rating Curve= 0 ,0
Exp/Cntr(USF)=0,0
Exp/Cntr=0.3,0.1

Type RM Length L Ch R = 1 ,8615    ,272.9,272.9,272.9
XS GIS Cut Line= 4
2204254.52106456630440.3676881212204495.11262565630540.453585189
2204602.14992406630623.0605149992204864.63306595630727.612210607
#Sta/Elev= 30
       0 2504.48    12.5 2500.73    40.8 2497.05    69.2 2491.06    97.1 2483.43
   118.8 2474.65   140.4 2464.02   179.4 2450.18   203.8 2449.69   218.4 2447.66
   257.4 2446.48   264.7 2445.48   274.9 2442.43   281.8  2442.5     288  2443.7
   298.9 2442.14   307.4 2441.72     316 2442.08   324.6 2443.26   357.9 2444.19
   384.5  2443.2   401.5 2450.01   445.2 2462.27   492.7 2477.98   505.6 2483.19
   514.2 2485.28   527.1 2490.31   577.6 2504.52   639.1 2525.76   678.3  2538.2
#Mann= 3 ,-1,0
       0      .1       0   298.9    .045       0     316      .1       0
#XS Ineff= 2 , 0
                          360.84         2465.07
Permanent Ineff=
       F       F
Bank Sta=298.9,316
XS Rating Curve= 0 ,0
Exp/Cntr(USF)=0,0
Exp/Cntr=0.3,0.1

Type RM Length L Ch R = 1 ,8342    ,194.4,194.4,194.4
XS GIS Cut Line= 4
2204156.30305718630698.8076631162204340.75139279630778.961959584
2204589.40739531630787.4867046932204843.64808897630816.116552604
#Sta/Elev= 30
       0 2506.77      26 2496.59    36.1 2491.44    50.3 2489.63    69.6 2481.56
   123.3  2468.7   156.9 2457.07   165.9 2455.82   184.1 2449.46   201.1 2445.36
   228.6 2441.67   300.6 2441.31   328.6 2439.31   356.6 2439.49     364 2438.12
   372.6 2437.45   380.7 2438.27   388.6 2443.43   413.7  2446.2   440.7 2452.41
   452.7 2453.83   464.7 2458.86   480.9 2462.18   517.1 2472.03   533.2 2474.41
   553.3 2481.28   601.6 2493.11   645.9 2513.46   678.1 2526.59   705.8  2536.2
#Mann= 3 ,-1,0
       0      .1       0     364    .045       0   380.7      .1       0
Bank Sta=364,380.7
XS Rating Curve= 0 ,0
Exp/Cntr(USF)=0,0
Exp/Cntr=0.3,0.1

Type RM Length L Ch R = 1 ,8148    ,122,122,122
XS GIS Cut Line= 4
 2204156.0705783630706.0510510232204359.40301813630794.960673003
2204407.33690128630995.2006042432204759.10975346631053.185140317
#Sta/Elev= 30
       0 2506.61    20.7 2498.35    30.7 2492.52      45 2490.86    65.6 2482.14
   109.3 2470.48   122.4 2468.19   152.9 2456.72     166 2454.76   178.6 2449.86
   207.5 2442.26   244.8 2437.49   281.8 2434.81   318.8 2436.76   328.3 2433.36
   335.3 2432.33   345.5 2433.42   360.5 2436.99   373.7 2438.05   427.8 2436.28
     453 2436.84   504.1  2442.4   517.9 2442.53   538.2 2445.75   598.9 2460.39
     680 2481.53   704.3 2489.62   736.8 2498.74   765.1  2509.3   784.3 2515.27
#Mann= 3 ,-1,0
       0      .1       0   328.3    .045       0   345.5      .1       0
#XS Ineff= 2 , 0
          312.49 2446.55
Permanent Ineff=
       F       F
Bank Sta=328.3,345.5
XS Rating Curve= 0 ,0
Exp/Cntr(USF)=0,0
Exp/Cntr=0.3,0.1