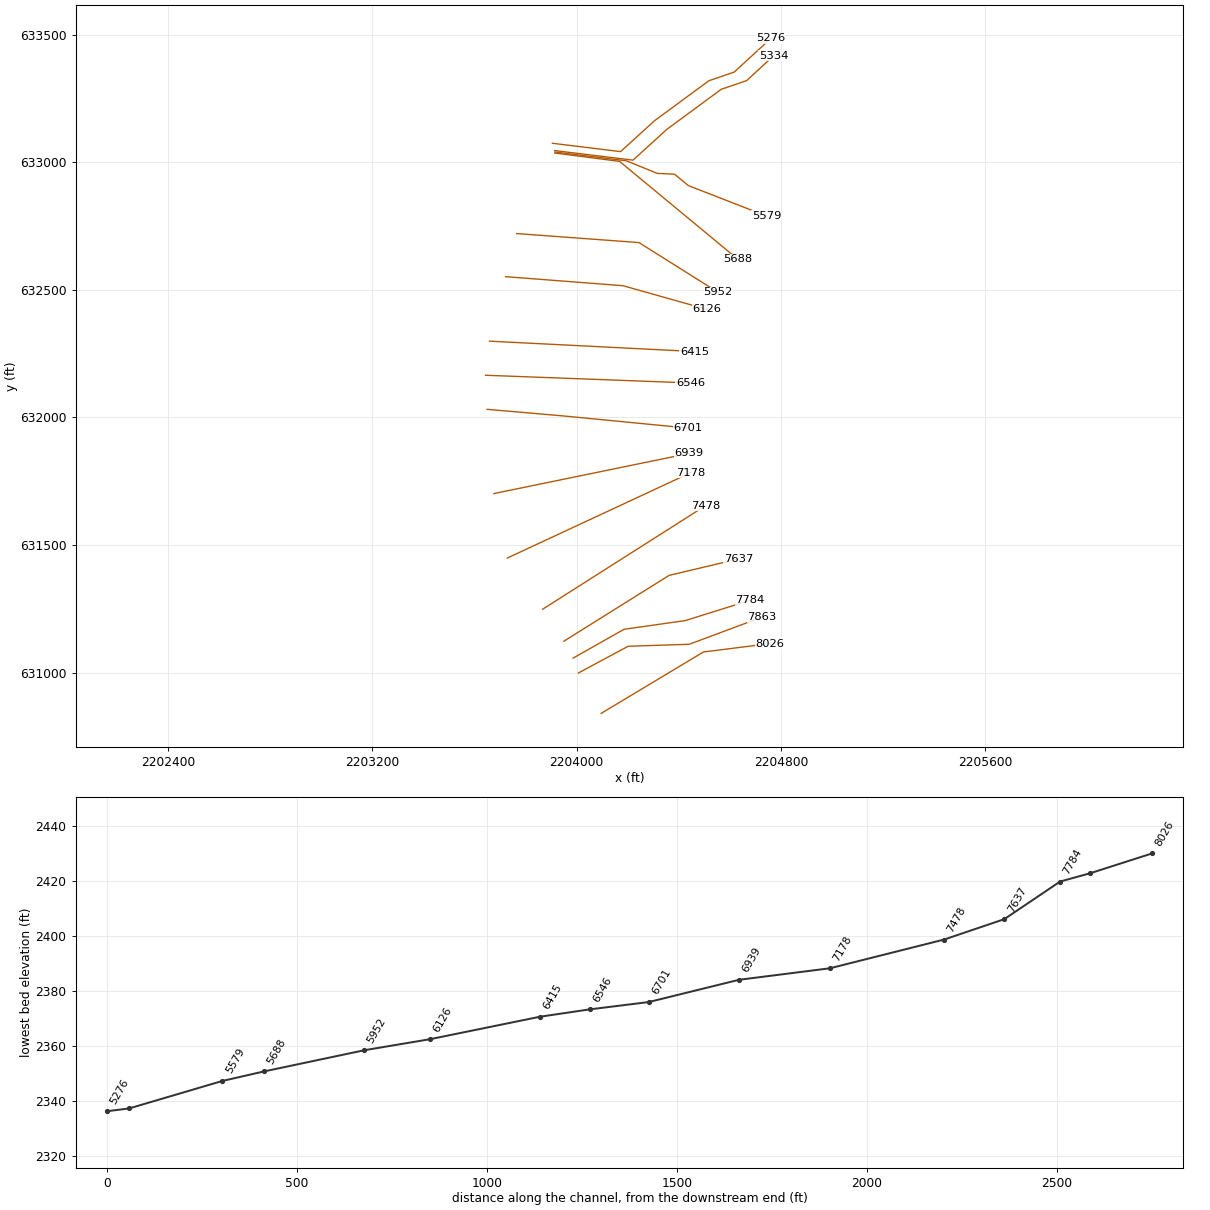
HEC-RAS study BEARCMPRN.prj: BEARCMPRN

--- BEARCMPRN.g01 (geometry) --- (continued)

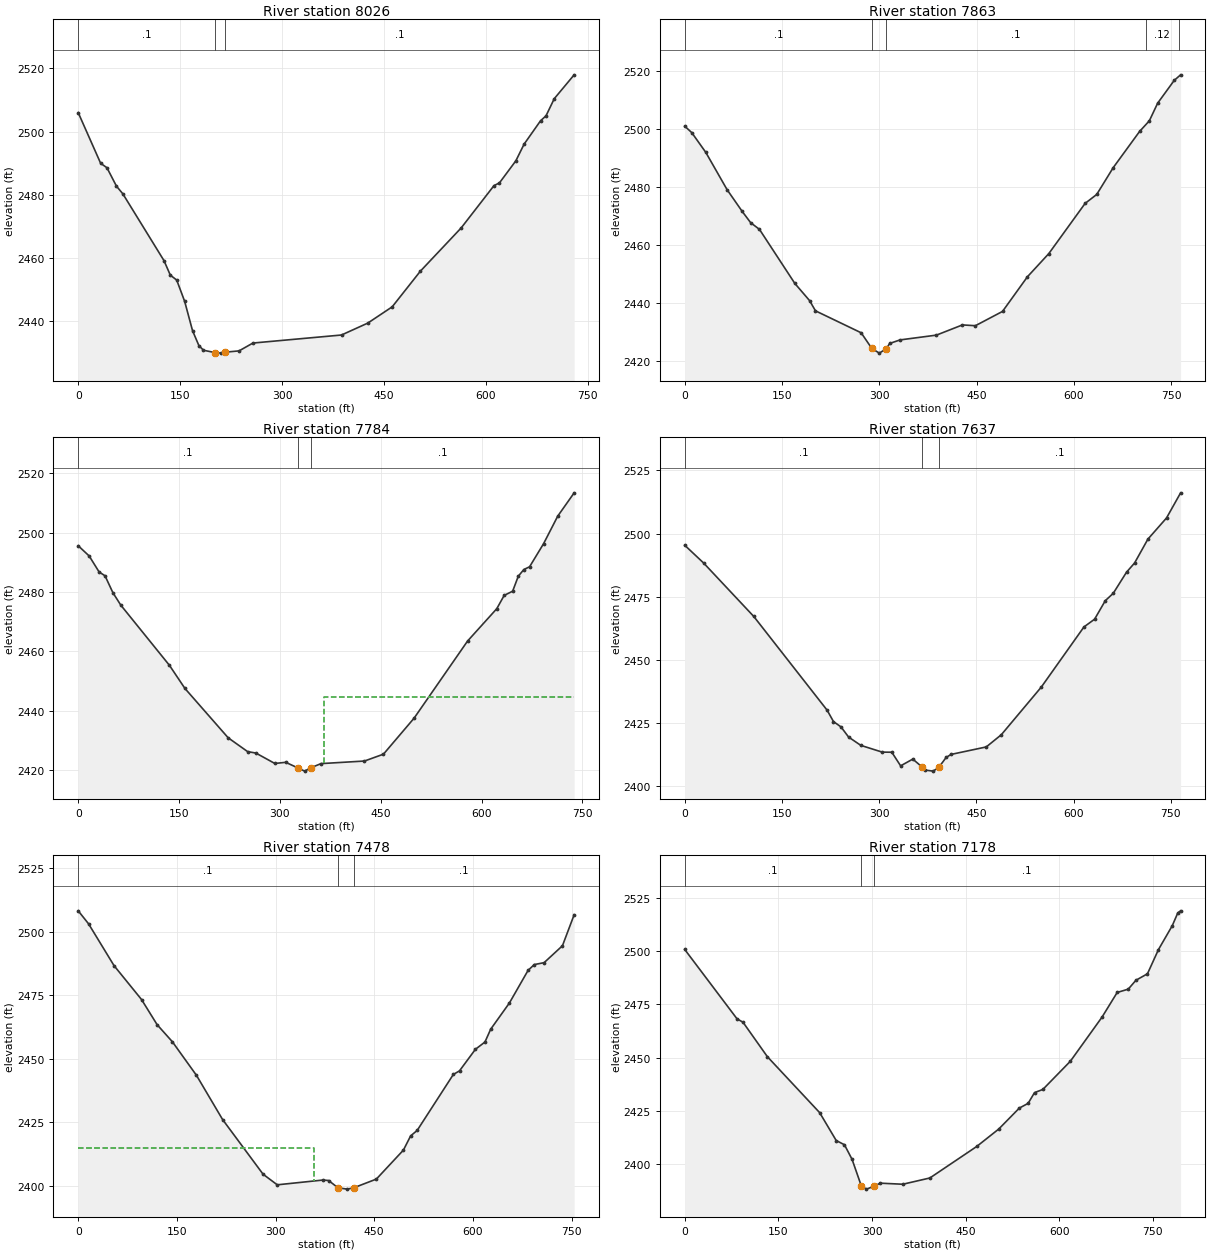
Type RM Length L Ch R = 1 ,8026    ,162.3,162.3,162.3
XS GIS Cut Line= 3
2204095.87142471630840.5397122182204496.72043663631081.122566184
2204757.27066166631113.855006515
#Sta/Elev= 30
       0    2506      33 2489.99    42.3 2488.57    56.3 2482.75    65.7 2480.32
   126.3 2459.18   135.6  2454.6     145 2453.04   156.7 2446.31   168.3 2437.04
   177.6 2432.34   184.4 2430.84     201 2430.12   210.3 2429.93   216.4 2430.23
   236.8 2430.64   257.2 2433.12   387.6 2435.66   426.3 2439.43   462.2 2444.57
   503.7 2455.85   563.8 2469.54   612.1 2482.92   620.1 2483.77   644.3 2490.77
   656.4 2496.03   680.6 2503.42   688.7    2505   700.8 2510.41   730.1 2517.96
#Mann= 3 ,-1,0
       0      .1       0     201    .045       0   216.4      .1       0
Bank Sta=201,216.4
XS Rating Curve= 0 ,0
Exp/Cntr(USF)=0,0
Exp/Cntr=0.3,0.1

Type RM Length L Ch R = 1 ,7863    ,79.8,79.8,79.8
XS GIS Cut Line= 4
2204006.55714418630998.7111453742204201.64248856631103.454954435
2204441.24395178631111.3107401152204725.36153386631217.363846787
#Sta/Elev= 30
       0 2501.04    10.9 2498.81    32.6 2491.97    65.4 2479.11    88.7 2471.61
   101.7 2467.74   115.3 2465.42   169.8 2446.78   192.5 2440.86   201.6 2437.33
     272 2429.76   288.5 2424.34     300 2422.74   310.8 2424.27     316 2426.08
     332  2427.3     388 2428.95   428.1 2432.47   448.1  2432.2   489.9 2437.13
   528.3 2449.08   561.3 2457.09   617.2 2474.39   635.1 2477.48   660.5 2486.72
   701.2 2499.22   716.2 2502.88     729 2508.96   754.6 2516.84   764.4 2518.74
#Mann= 5 ,-1,0
       0      .1       0   288.5    .045       0   310.8      .1       0
  711.16     .12       0  761.16      .1       0
Bank Sta=288.5,310.8
XS Rating Curve= 0 ,0
Exp/Cntr(USF)=0,0
Exp/Cntr=0.3,0.1

Type RM Length L Ch R = 1 ,7784    ,147,147,147
XS GIS Cut Line= 4
2203985.98260582631057.0507760552204185.44940991631169.927339611
2204425.11882568631203.9449341082204679.47765726631283.577030316
#Sta/Elev= 30
       0 2495.58    16.3 2492.14    31.1 2486.75    39.9 2485.46    51.6 2479.77
    63.3  2475.6   135.8 2455.29   158.8 2447.52   223.1 2430.91   252.1 2426.25
   264.3 2425.78   292.5 2422.27   308.7 2422.66   326.5  2420.8   336.9 2419.69
   346.3 2420.84   361.2 2422.22   425.9 2423.09   454.1  2425.4   499.6  2437.5
   579.3 2463.51   622.7 2474.39   633.7 2478.86   646.3 2480.28   654.7 2485.32
     663 2487.58   671.5  2488.5   692.4 2496.31   713.4 2505.56   737.8  2513.4
#Mann= 3 ,-1,0
       0      .1       0   326.5    .045       0   346.3      .1       0
#XS Ineff= 2 , 0
                          365.76         2444.64
Permanent Ineff=
       F       F
Bank Sta=326.5,346.3
XS Rating Curve= 0 ,0
Exp/Cntr(USF)=0,0
Exp/Cntr=0.3,0.1

Type RM Length L Ch R = 1 ,7637    ,158.5,158.5,158.5
XS GIS Cut Line= 3
2203949.79550517631123.3072318672204362.22425335631381.238861677
2204633.24885929631445.394444726
#Sta/Elev= 30
       0 2495.38    29.2 2488.33   106.6 2467.18   219.8 2430.08   229.5 2425.61
   241.1  2423.5   252.9 2419.46   271.7 2416.19   304.7 2413.52   319.5 2413.48
   333.1 2408.09   351.9 2410.76   366.8  2407.5   370.8 2406.42   383.3    2406
     392  2407.5   403.3  2411.4   410.9 2412.61   465.2 2415.57   488.4 2420.39
   550.1 2439.25   615.9 2463.04   632.3  2466.1   648.8 2473.42   661.1 2476.35
   681.6 2484.71     694 2488.34   714.5 2497.76   743.3 2506.16     765 2516.09
#Mann= 3 ,-1,0
       0      .1       0   366.8    .045       0     392      .1       0
Bank Sta=366.8,392
XS Rating Curve= 0 ,0
Exp/Cntr(USF)=0,0
Exp/Cntr=0.3,0.1

Type RM Length L Ch R = 1 ,7478    ,300.2,300.2,300.2
XS GIS Cut Line= 2
2203866.94828465 631248.712660682204503.26692469631653.285623174
#Sta/Elev= 30
       0  2508.3    15.7 2503.19    54.5 2486.68    96.3 2473.32     120  2463.4
   143.2 2456.67   179.8 2443.44   219.5 2426.02   281.1 2404.45   302.6 2400.28
   372.1 2402.16   380.7 2401.98   394.9 2399.11   409.1 2398.58  419.542399.168
   453.3 2402.54   494.4 2413.96   505.4 2419.57   515.3 2421.71   570.3 2443.78
   579.7 2445.21   603.9 2453.71   618.4 2456.58   627.1 2461.63   655.6 2471.98
     684 2484.85   693.5 2487.12   708.3 2487.86   736.2 2494.53     754 2506.76
#Mann= 3 ,-1,0
       0      .1       0   394.9    .045       0  419.54      .1       0
#XS Ineff= 2 , 0
           358.7 2414.76
Permanent Ineff=
       F       F
Bank Sta=394.9,419.54
XS Rating Curve= 0 ,0
Exp/Cntr(USF)=0,0
Exp/Cntr=0.3,0.1

Type RM Length L Ch R = 1 ,7178    ,239.3,239.3,239.3
XS GIS Cut Line= 2
2203728.16273765631449.0351955072204448.27642494631784.215384499
#Sta/Elev= 30
       0 2500.86    83.8 2468.23    93.4 2466.62   132.4 2450.43   216.2  2424.1
   242.7    2411   255.9    2409   268.1 2402.14   283.1 2389.49   291.2 2388.14
  302.732389.448   313.3 2390.94   349.4 2390.44   392.7 2393.38   467.7 2408.19
     503 2416.39     536 2426.25   550.1 2428.48   560.3 2433.52   573.6    2435
   617.7 2448.27   668.5 2469.05   692.7 2480.62   710.4 2482.16   722.7 2486.34
   741.2  2489.4   758.8 2500.77   780.9    2512   789.8 2518.03   794.3    2519
#Mann= 3 ,-1,0
       0      .1       0   283.1    .045       0  302.73      .1       0
Bank Sta=283.1,302.73
XS Rating Curve= 0 ,0
Exp/Cntr(USF)=0,0
Exp/Cntr=0.3,0.1

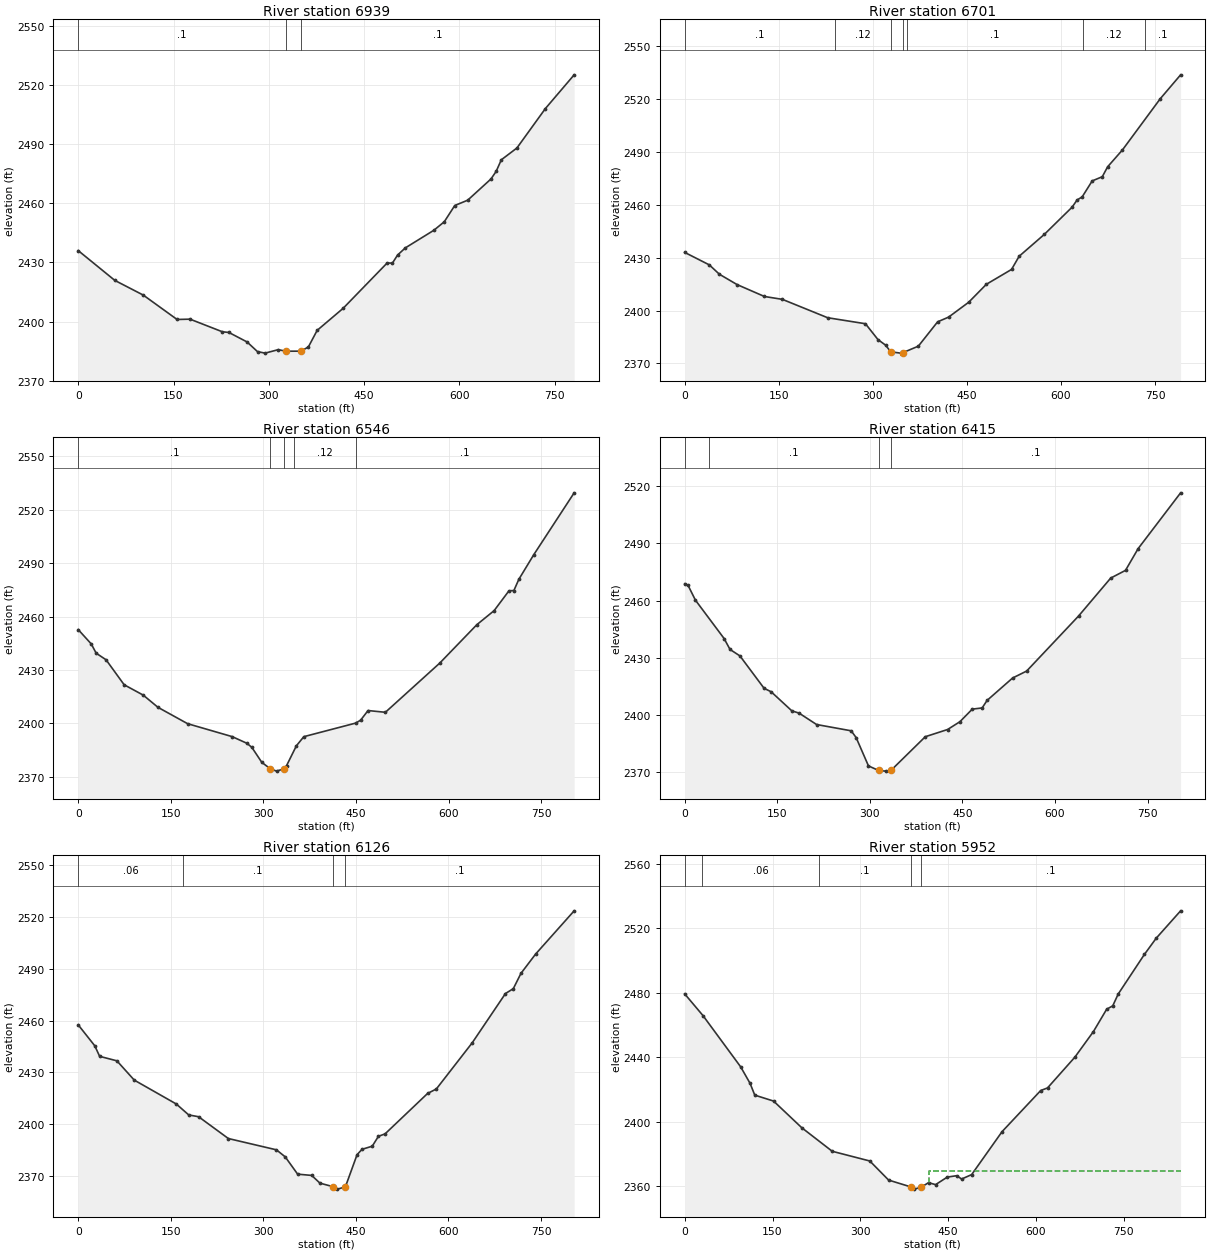
Type RM Length L Ch R = 1 ,6939    ,237.7,237.7,237.7
XS GIS Cut Line= 2
2203675.79083312631701.7296348642204440.42063926631858.845348454
#Sta/Elev= 30
       0 2436.05    57.6 2420.91   102.5 2413.42   155.6 2401.05     176 2401.21
   226.8 2394.81   237.2 2394.45   265.8 2389.62   282.2 2384.71   294.2 2383.95
   314.8 2385.71   327.1 2384.92   350.7 2384.96   362.3  2387.1   376.1 2395.52
   416.9 2406.69   486.3 2429.77   494.5 2429.66   502.7  2433.8   514.9 2437.43
   559.8 2446.38   576.2  2450.7   592.7 2458.96     613 2461.65   649.7 2472.45
   657.8 2476.29     666 2482.19   690.5 2488.18   735.4 2508.25   780.6 2525.36
#Mann= 3 ,-1,0
       0      .1       0   327.1    .045       0   350.7      .1       0
Bank Sta=327.1,350.7
XS Rating Curve= 0 ,0
Exp/Cntr(USF)=0,0
Exp/Cntr=0.3,0.1

Type RM Length L Ch R = 1 ,6701    ,155.2,155.2,155.2
XS GIS Cut Line= 3
2203648.99604187632031.7494728012203952.69452055632005.369807457
2204436.49274642631958.351967061
#Sta/Elev= 30
       0 2432.99    39.3  2425.9    55.4 2420.59    83.5 2414.74   127.2 2407.98
   155.8 2406.35     228 2395.93   288.3 2392.52   308.3 2383.51   320.4 2380.38
328.65762376.574   344.5 2375.85 348.2832376.168   372.6 2379.79   403.4 2393.61
   420.9 2396.28     453 2404.73   481.1 2414.89   521.3 2423.33   533.4  2430.8
   573.6 2443.22   617.8 2458.63   625.8 2462.72   633.9 2464.48   649.9 2473.54
     666 2475.92   674.5 2481.54   698.2 2491.14   758.4 2520.14   790.9 2533.71
#Mann= 7 ,-1,0
       0      .1       0     240     .12       0328.6576    .045       0
 348.283     .12       0  354.84      .1       0  634.84     .12       0
  734.84      .1       0
Bank Sta=328.6576,348.283
XS Rating Curve= 0 ,0
Exp/Cntr(USF)=0,0
Exp/Cntr=0.3,0.1

Type RM Length L Ch R = 1 ,6546    ,130.6,130.6,130.6
XS GIS Cut Line= 2
2203643.05839279632165.2209899542204445.65782971632135.107144849
#Sta/Elev= 30
       0 2452.72    21.1 2444.66    29.1 2439.45    45.1 2435.75    74.4 2421.71
   105.3  2415.9   129.2 2409.03   177.2 2399.84   249.3 2392.58   273.3 2388.82
   281.3  2386.5   297.3 2378.13  311.15 2374.49   321.2 2373.19   332.9 2374.45
   337.4 2376.24   353.4 2387.45   365.4 2392.55   449.4 2400.18   457.4 2401.83
   469.4 2407.23   497.5 2406.25   585.5 2433.88   645.7  2455.5   673.6 2463.37
   697.6  2474.5   705.6 2474.67   713.6 2480.95   737.6 2494.69   803.2 2529.56
#Mann= 5 ,-1,0
       0      .1       0  311.15    .045       0   332.9      .1       0
     350     .12       0     450      .1       0
Bank Sta=311.15,332.9
XS Rating Curve= 0 ,0
Exp/Cntr(USF)=0,0
Exp/Cntr=0.3,0.1

Type RM Length L Ch R = 1 ,6415    ,289.6,289.6,289.6
XS GIS Cut Line= 2
2203658.76996415632298.7693465052204461.36940107632258.181120495
#Sta/Elev= 30
       0 2468.84     5.4 2468.03    17.4 2460.25    63.9 2440.09    73.5 2434.36
    89.5 2430.99   128.7 2413.97   140.1 2412.17   173.6 2402.16   185.4 2400.95
   213.7 2394.98   269.8 2391.68   277.8 2388.14   297.8 2373.26   314.12370.881
   325.8 2370.52   334.22370.887   389.9 2388.58     426 2392.36     446 2396.46
     466 2403.05     482 2403.68     490 2407.63   531.3 2419.37   554.1 2423.03
   638.2  2451.9   690.3 2471.82   714.3 2475.87   734.8  2487.3   803.6 2516.56
#Mann= 4 ,-1,0
       0     .06       0      40      .1       0   314.1    .045       0
   334.2      .1       0
Bank Sta=314.1,334.2
XS Rating Curve= 0 ,0
Exp/Cntr(USF)=0,0
Exp/Cntr=0.3,0.1

Type RM Length L Ch R = 1 ,6126    ,173.4,173.4,173.4
XS GIS Cut Line= 3
2203721.61624958632551.4637858622204181.17971183632516.112750305
2204511.12271037632423.152619764
#Sta/Elev= 30
       0 2457.59    26.9 2445.42    34.7 2439.34    62.7 2436.73    90.8 2425.56
     159 2411.69   179.1 2405.36   195.1 2404.32   243.3 2391.68   321.2 2385.13
   335.5 2381.04   355.6 2371.02   378.4 2370.29   391.7 2365.82   413.2 2363.73
   419.8 2362.34   432.9 2363.56   451.9 2382.32   459.9 2385.42   476.5 2387.24
   486.5 2392.96   497.3 2394.38   566.2 2417.82   580.4 2420.42   638.6 2447.23
   692.4 2475.76   705.1 2478.58   717.5 2487.45   741.3 2498.66   803.7 2523.71
#Mann= 4 ,-1,0
       0     .06       0     170      .1       0   413.2    .045       0
   432.9      .1       0
Bank Sta=413.2,432.9
XS Rating Curve= 0 ,0
Exp/Cntr(USF)=0,0
Exp/Cntr=0.3,0.1

Type RM Length L Ch R = 1 ,5952    ,264,264,264
XS GIS Cut Line= 3
2203764.82307082632720.3631779712204244.02599727632685.012142413
2204554.32953161632489.926798039
#Sta/Elev= 30
       0 2479.37    31.4 2465.84    95.6 2434.14   111.7 2423.88   119.7 2416.59
   151.8 2412.91   199.9  2396.4     252 2381.77   316.2 2375.75   348.3 2363.92
  386.412359.664   392.4 2358.31   404.4 2359.62   416.5 2362.32   428.5  2361.1
   448.6 2365.79   464.6 2366.63     473 2364.58   490.1 2367.31   542.1 2393.97
   608.1 2419.46   619.7 2421.05   666.2 2440.04   698.1 2456.01   720.7 2469.85
   731.1 2471.96   740.5 2479.33   785.1 2503.81   805.4 2513.92     847 2530.86
#Mann= 5 ,-1,0
       0     .08       0      30     .06       0     230      .1       0
  386.41    .045       0   404.4      .1       0
#XS Ineff= 2 , 0
                          417.59         2369.49
Permanent Ineff=
       F       F
Bank Sta=386.41,404.4
XS Rating Curve= 0 ,0
Exp/Cntr(USF)=0,0
Exp/Cntr=0.3,0.1

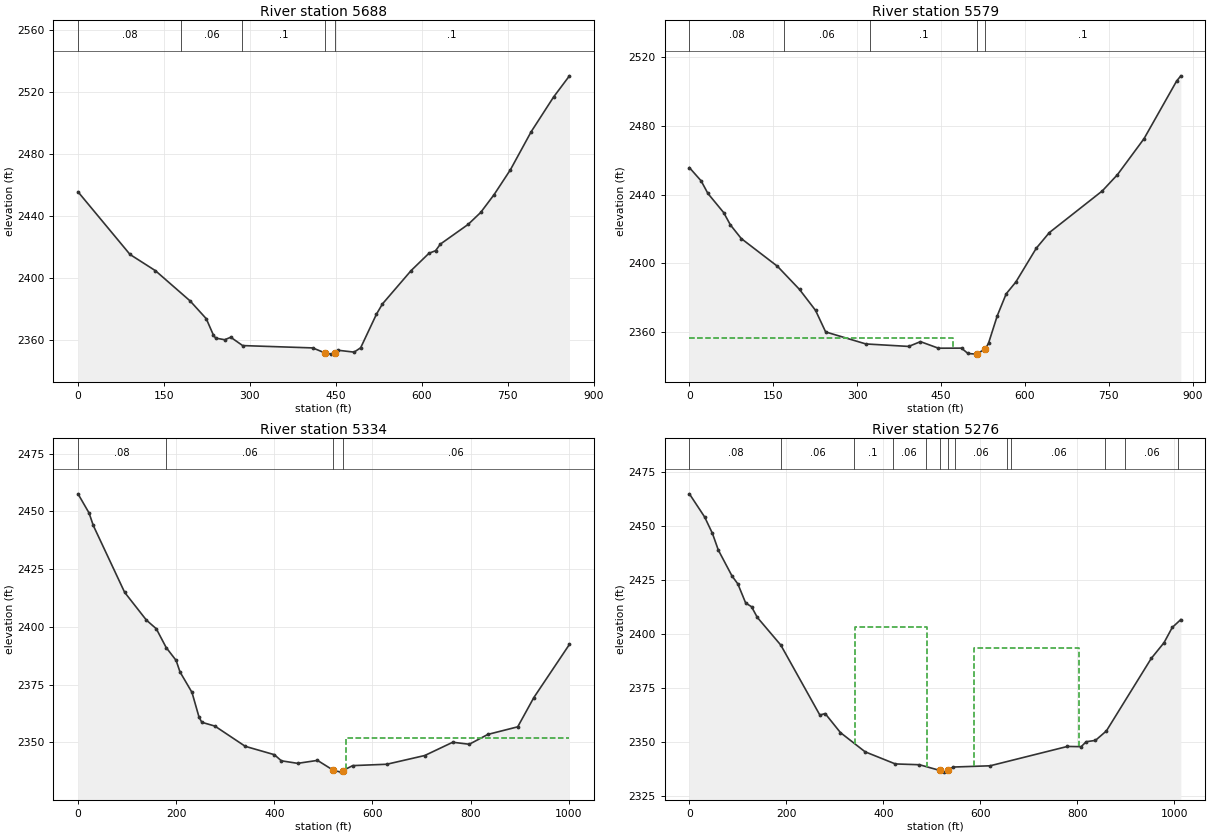
Type RM Length L Ch R = 1 ,5688    ,109.3,109.3,109.3
XS GIS Cut Line= 3
2203914.08299873633035.903902764 2204168.0867357633003.171462433
2204631.57809079632619.547261751
#Sta/Elev= 30
       0 2455.41    90.8 2414.95   135.2 2404.46   195.7 2384.95   223.9 2373.46
     236  2363.2   240.1 2360.97   256.1 2359.89   266.6  2361.5   287.4 2356.12
   409.8 2354.61   430.9 2351.39   442.2  2350.6   447.9 2351.49   453.6 2353.11
     482 2351.89   493.4 2354.72     521 2376.42   531.4 2383.01   581.5 2404.57
   612.7 2415.74   624.1 2417.36   632.6 2421.66   680.9 2434.33   702.8 2442.04
   726.3  2453.6   754.8 2469.67     791  2494.2   830.1  2516.6   857.8 2530.28
#Mann= 5 ,-1,0
       0     .08       0     180     .06       0   286.1      .1       0
   430.9    .045       0   447.9      .1       0
Bank Sta=430.9,447.9
XS Rating Curve= 0 ,0
Exp/Cntr(USF)=0,0
Exp/Cntr=0.3,0.1

Type RM Length L Ch R = 1 ,5579    ,245.2,245.2,245.2
BEGIN DESCRIPTION:
Structure XS 4
END DESCRIPTION:
XS GIS Cut Line= 6
2203915.30878466633039.6821293752204194.51001195633005.466142193
2204315.70714919632956.1229355832204383.49931129 632952.90219277
2204437.40564401632908.2531194982204743.11027147632789.332155416
#Sta/Elev= 30
       0  2455.8      21 2448.06    33.1 2440.74    61.3 2429.58    73.4 2422.38
    92.8 2414.45   157.4 2398.32   196.9 2384.81   225.6  2372.6   243.6 2360.07
   315.5 2353.07   392.1 2351.62   413.1 2354.41   445.2 2350.59   486.5 2350.64
   497.9 2347.53   512.1 2347.14 513.6652347.257 528.9752350.123   534.8 2353.51
   550.5 2369.57   566.4 2382.29   583.6 2389.13   620.2 2408.85   643.6 2417.96
   738.1 2442.19   765.2 2451.64   812.8 2472.65   871.1 2506.24   878.6 2509.25
#Mann= 5 ,-1,0
       0     .08       0     170     .06       0  322.52      .1       0
 513.665    .045       0 528.975      .1       0
#XS Ineff= 2 , 0
          471.77 2356.62
Permanent Ineff=
       F       F
Bank Sta=513.665,528.975
XS Rating Curve= 0 ,0
Exp/Cntr(USF)=0,0
Exp/Cntr=0.3,0.1

Type RM Length L Ch R = 1 ,5334    ,58.2,58.2,58.2
BEGIN DESCRIPTION:
Structure XS 3
END DESCRIPTION:
XS GIS Cut Line= 6
2203913.73674054633045.4233244322204220.78371114633007.990853807
2204353.02277008633128.4462342252204566.43828104633285.561947815
2204665.94489964 633319.603685762204771.19238718633416.592517496
#Sta/Elev= 30
       0 2457.61    22.6  2449.3    31.1 2443.94    95.1 2414.96   139.5 2402.93
   159.6 2399.21   179.8 2391.05   199.9 2385.53     208 2380.48   232.3 2371.67
   246.6 2361.02   252.3 2358.73     279 2357.08   340.9 2348.32   400.2  2344.7
   414.5 2342.05   447.7 2340.95   488.1 2342.23  520.692337.908   536.1 2337.15
   539.8 2337.82   559.9 2339.97   629.3 2340.56   706.7 2344.34   763.8 2350.09
   797.4 2349.21   835.4 2353.48   896.2 2356.76   929.1 2369.45  1001.6 2392.45
#Mann= 4 ,-1,0
       0     .08       0     180     .06       0  520.69    .045       0
   539.8     .06       0
#XS Ineff= 2 , 0
                          545.85          2352.1
Permanent Ineff=
       F       F
Bank Sta=520.69,539.8
XS Rating Curve= 0 ,0
Exp/Cntr(USF)=0,0
Exp/Cntr=0.3,0.1

Type RM Length L Ch R = 1 ,5276    ,220.6,220.6,220.6
BEGIN DESCRIPTION:
Structure XS 2
END DESCRIPTION:
XS GIS Cut Line= 6
2203904.93198041633074.0785013722204172.02869351633041.346061041
2204304.26775245633161.8014414592204517.68326341633318.917155049
2204617.18988201633352.9588929942204761.21261947633485.197951932
#Sta/Elev= 30
       0 2464.83    31.5 2454.11    47.6  2446.5    59.7 2438.81    87.9 2426.85
     100 2423.16   116.1 2414.34   128.2 2412.62   140.1 2407.69   188.6 2394.87
   269.1 2362.53   280.1 2363.21   311.6 2354.41   362.5 2345.52   424.8 2339.92
   474.6 2339.55   515.92336.956   526.2 2336.13   533.6 2336.95     544 2338.48
   620.3 2339.06   779.8 2348.01   808.1  2347.9   818.5 2350.19   837.5  2350.8
   860.1 2355.17   952.6  2388.7     979 2395.99     996 2403.04  1013.7  2406.7
#Mann= 13 ,-1,0
       0     .08       0     190     .06       0  339.09      .1       0
  419.09     .06       0  487.97      .1       0   515.9    .045       0
   533.6      .1       0  547.97     .06       0  654.19      .1       0
  664.19     .06       0  858.21      .1       0  898.21     .06       0
 1008.21      .1       0
#XS Ineff= 2 ,-1
  340.98  489.62 2403.17  587.98  804.37 2393.46
Permanent Ineff=
       F       F
Bank Sta=515.9,533.6
XS Rating Curve= 0 ,0
Exp/Cntr(USF)=0,0
Exp/Cntr=0.3,0.1