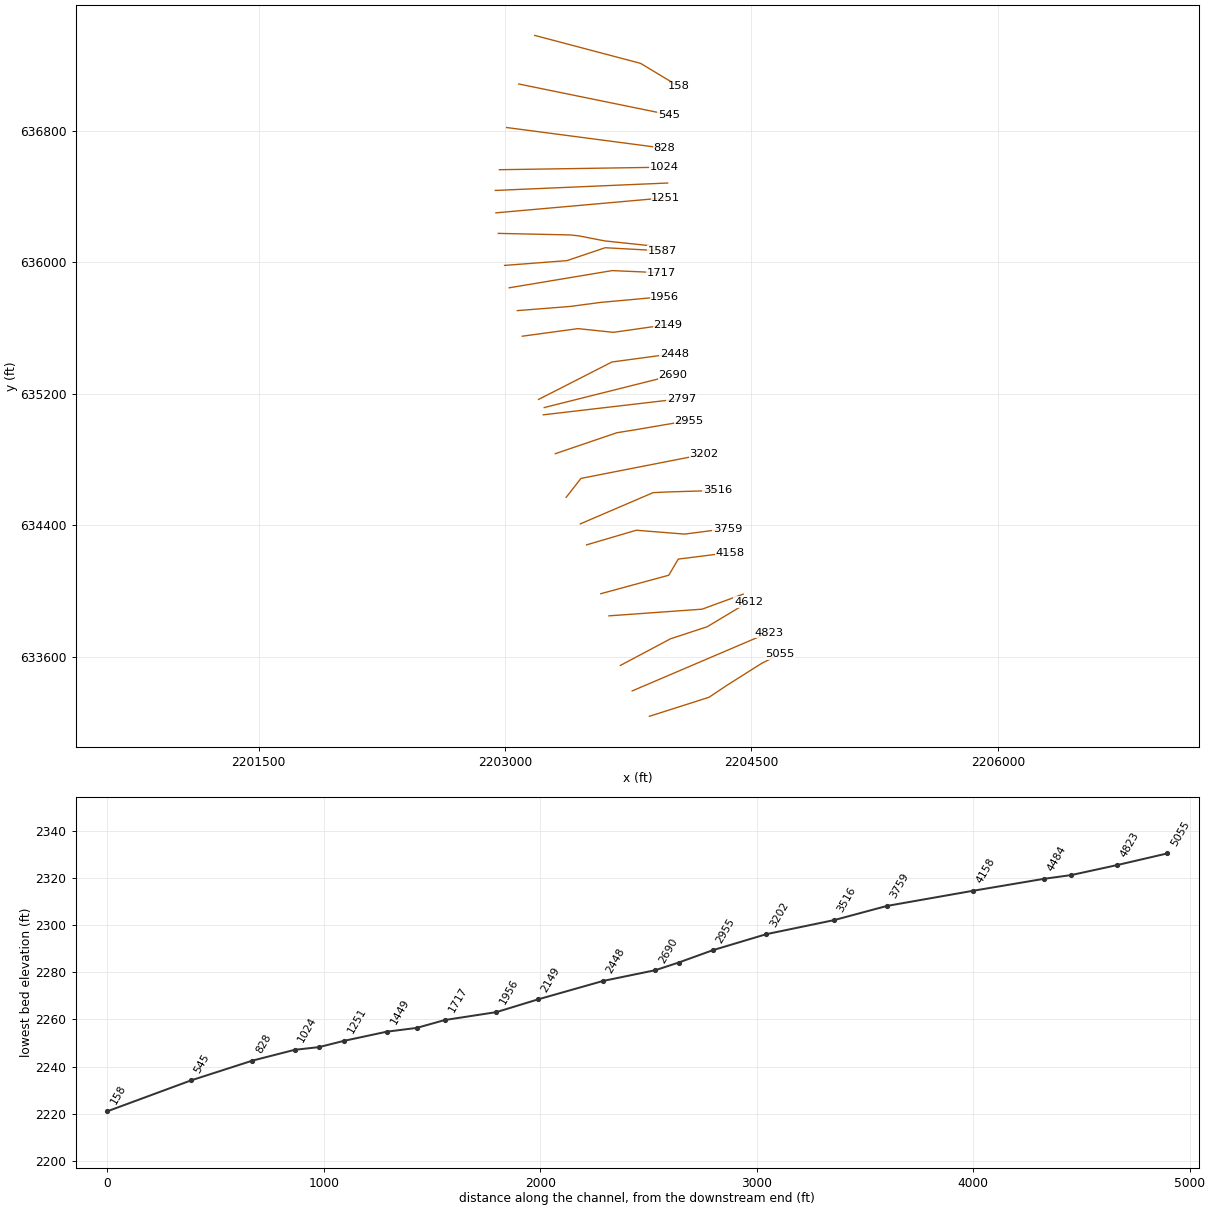
HEC-RAS study BEARCMPRN.prj: BEARCMPRN

--- BEARCMPRN.g01 (geometry) --- (continued)

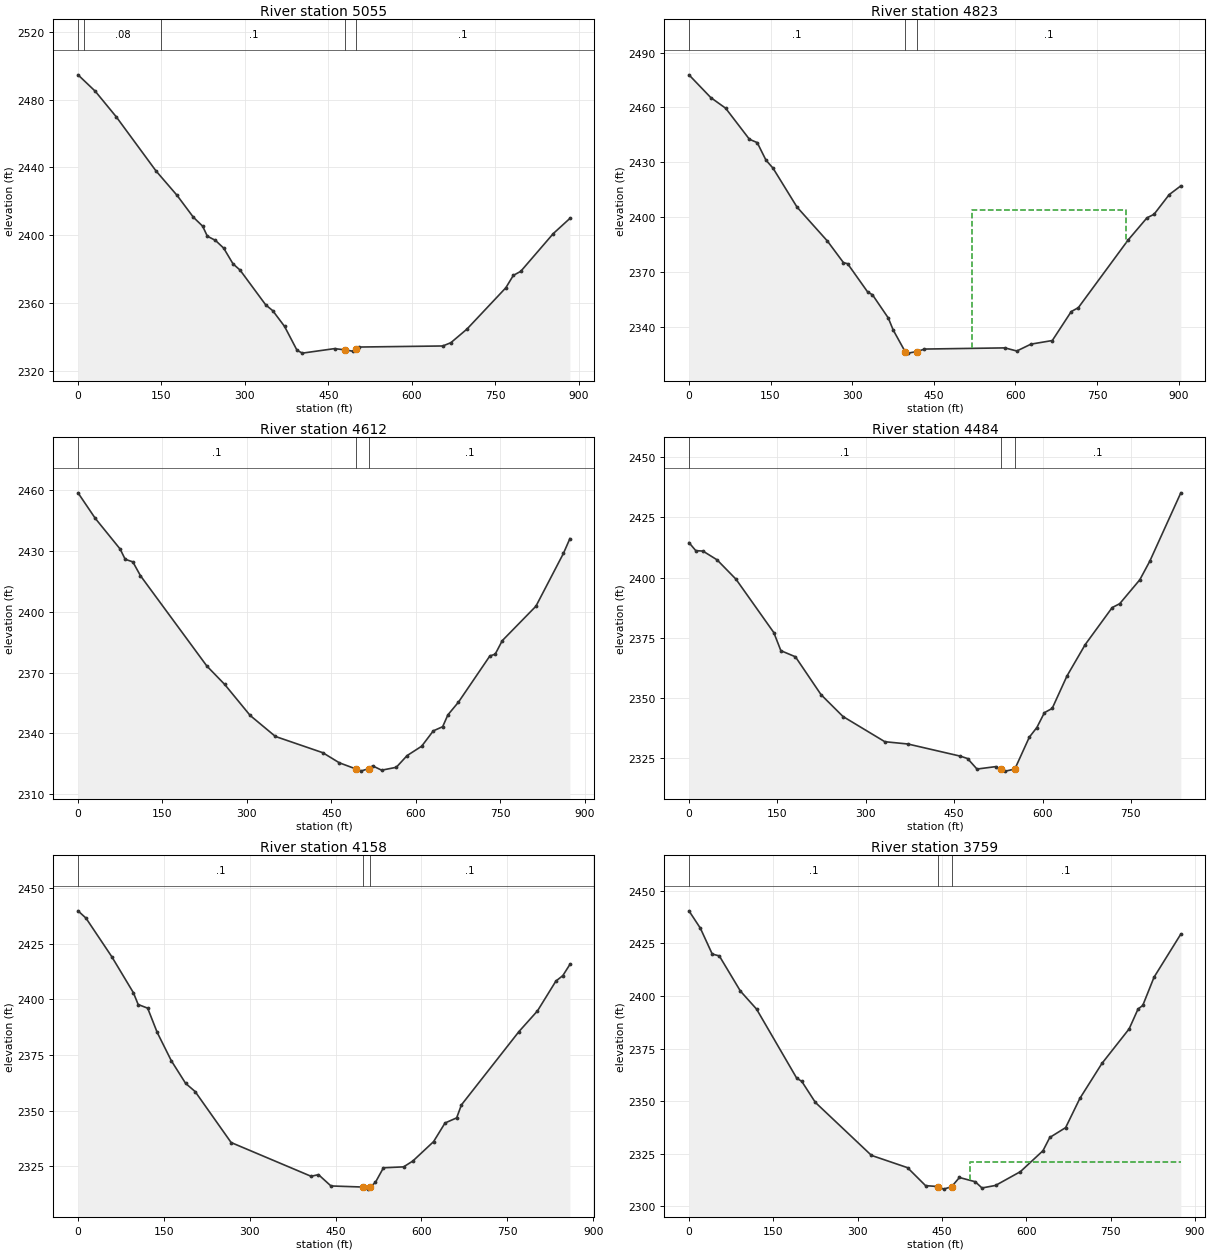
Type RM Length L Ch R = 1 ,5055    ,231.6,231.6,231.6
BEGIN DESCRIPTION:
Structure XS 1
END DESCRIPTION:
XS GIS Cut Line= 5
2203878.73196317633236.2264375912204241.57005446633351.939729868
 2204349.0016885633423.7795028612204560.14349169633557.290037161
2204670.76179108633613.278317813
#Sta/Elev= 30
       0 2494.64    30.9 2484.99    68.8 2469.84   140.1 2437.97   177.9 2423.57
   207.2 2410.67     224 2405.34   232.4 2399.44     247 2396.96   261.8 2392.38
   278.6  2383.1   291.2 2379.45   337.4 2358.88     350 2355.48   371.2  2346.2
   393.6 2332.11   403.2 2330.45     461 2333.11   480.2 2332.36   494.7 2331.53
   499.5 2332.71   504.3 2334.04   655.5 2334.67     670  2336.6   698.9 2344.62
   768.8 2369.01   782.3 2376.32   795.6  2378.7   854.1 2400.99   883.9 2409.92
#Mann= 5 ,-1,0
       0      .1       0      10     .08       0     150      .1       0
   480.2    .045       0   499.5      .1       0
Bank Sta=480.2,499.5
XS Rating Curve= 0 ,0
Exp/Cntr(USF)=0,0
Exp/Cntr=0.3,0.1

Type RM Length L Ch R = 1 ,4823    ,211.4,211.4,211.4
XS GIS Cut Line= 2
2203773.98815411633390.7235559542204605.39213853633745.543209145
#Sta/Elev= 30
       0 2477.87    40.1 2465.42    67.4  2459.6   111.1  2442.6   125.5 2440.75
   141.5 2431.18   154.6 2426.73   198.6 2405.47   254.6 2386.82     284 2375.04
   291.6 2374.47   328.6 2358.92   337.3 2357.46   366.3 2344.78   375.4 2338.15
  397.332326.327   402.5 2325.51  419.532326.391   432.9 2327.74   580.8 2328.38
   602.5 2326.67   628.6 2330.43   667.8 2332.41   702.6 2348.27   715.6 2350.38
   806.9 2387.35   841.7 2399.55   854.8 2401.53   882.6 2412.28     904 2417.08
#Mann= 3 ,-1,0
       0      .1       0  397.33    .045       0  419.53      .1       0
#XS Ineff= 1 ,-1
  520.95  803.28 2404.01
Permanent Ineff=
       F
Bank Sta=397.33,419.53
XS Rating Curve= 0 ,0
Exp/Cntr(USF)=0,0
Exp/Cntr=0.3,0.1

Type RM Length L Ch R = 1 ,4612    ,128.2,128.2,128.2
XS GIS Cut Line= 4
2203702.11883611633545.8382593112204007.45074045633708.073821842
2204230.48215977633781.264810221 2204481.9784748633932.179892054
#Sta/Elev= 30
       0 2458.78    30.6 2446.19    74.8 2431.02    83.8 2425.95    97.4 2424.67
     111 2417.81   228.8 2373.24   260.5 2364.14   305.8 2348.79   350.7 2338.41
   434.9 2330.38   464.2  2325.4  493.342322.389   502.3 2321.28  517.032322.557
   523.3 2323.89   539.4 2321.74   565.4 2323.17   584.6 2328.95   610.5 2333.59
   631.2 2341.18   647.8 2343.23   657.1 2349.08   675.8 2355.34   731.7  2378.2
   741.1 2379.05   753.7 2385.75   813.5 2402.77   862.4 2428.89   873.8 2436.15
#Mann= 3 ,-1,0
       0      .1       0  493.34    .045       0  517.03      .1       0
Bank Sta=493.34,517.03
XS Rating Curve= 0 ,0
Exp/Cntr(USF)=0,0
Exp/Cntr=0.3,0.1

Type RM Length L Ch R = 1 ,4484    ,325.6,325.6,325.6
XS GIS Cut Line= 3
2203632.58401188633847.6684229782204199.50987842633888.256648989
2204449.58572255633979.907481916
#Sta/Elev= 30
       0  2414.5    11.6 2411.15    23.7 2410.98    47.7 2407.34    79.8 2399.31
     144 2377.15     156 2369.64   180.7  2367.1   224.2 2351.37   261.4 2342.32
   332.4 2331.86   371.5 2330.91   460.8 2325.85   472.8 2324.87   488.8 2320.51
   520.6 2321.52   528.7 2320.55     537 2319.65     553  2320.5   577.6 2333.75
   590.4 2337.75   603.2 2343.91   616.4 2345.68   641.5 2359.14   672.5 2372.19
   718.2 2387.52     731 2389.14   765.1 2399.07   782.1 2406.81   834.7 2435.15
#Mann= 3 ,-1,0
       0      .1       0   528.7    .045       0     553      .1       0
Bank Sta=528.7,553
XS Rating Curve= 0 ,0
Exp/Cntr(USF)=0,0
Exp/Cntr=0.3,0.1

Type RM Length L Ch R = 1 ,4158    ,398.9,398.9,398.9
XS GIS Cut Line= 4
2203582.74559823633982.3558684532203996.56874836634094.859884467
2204054.35560236634193.0744719532204368.40927053634232.601921273
#Sta/Elev= 30
       0 2439.91    13.9 2436.63    58.9  2419.3    96.8 2403.03   105.1 2397.73
   121.7 2396.09   138.3 2385.19   163.1 2372.38     188 2362.23   204.6 2358.55
   267.5 2335.59   407.2 2320.39   420.1 2321.13   441.9 2316.04   497.5 2315.55
   505.8 2314.61   510.4 2315.49   519.7 2317.72   533.6 2324.22   568.8 2324.63
   584.9 2327.26   621.2    2336   641.2 2344.39   661.5 2346.69   669.8 2352.53
   770.4 2385.57   802.7 2394.86   834.9 2408.29     847 2410.75   859.3 2415.77
#Mann= 3 ,-1,0
       0      .1       0   497.5    .045       0   510.4      .1       0
Bank Sta=497.5,510.4
XS Rating Curve= 0 ,0
Exp/Cntr(USF)=0,0
Exp/Cntr=0.3,0.1

Type RM Length L Ch R = 1 ,3759    ,243.5,243.5,243.5
XS GIS Cut Line= 4
 2203496.4170601 634279.736635352203798.86480876634368.768873051
2204093.45677174634345.2015160132204355.31629439634379.243253957
#Sta/Elev= 30
       0 2440.47    20.3 2432.21    41.4 2419.92      54 2419.04    91.5 2402.33
   120.2 2393.77   191.6 2360.95   200.7 2359.38   224.9 2349.37   324.6  2324.2
   388.8 2318.36   420.9 2309.81   443.6 2309.39     453 2308.16   467.12309.297
   481.1 2313.69   509.3 2311.67   521.2 2308.71   545.3 2309.91   589.5 2316.46
   629.7 2326.42   641.8 2332.72     670  2337.4   695.3 2351.28   734.5 2367.89
     783 2384.36   798.8 2393.79   807.2 2395.49   827.3 2408.94   874.9 2429.41
#Mann= 3 ,-1,0
       0      .1       0   443.6    .045       0   467.1      .1       0
#XS Ineff= 2 , 0
                          499.64         2320.97
Permanent Ineff=
       F       F
Bank Sta=443.6,467.1
XS Rating Curve= 0 ,0
Exp/Cntr(USF)=0,0
Exp/Cntr=0.3,0.1

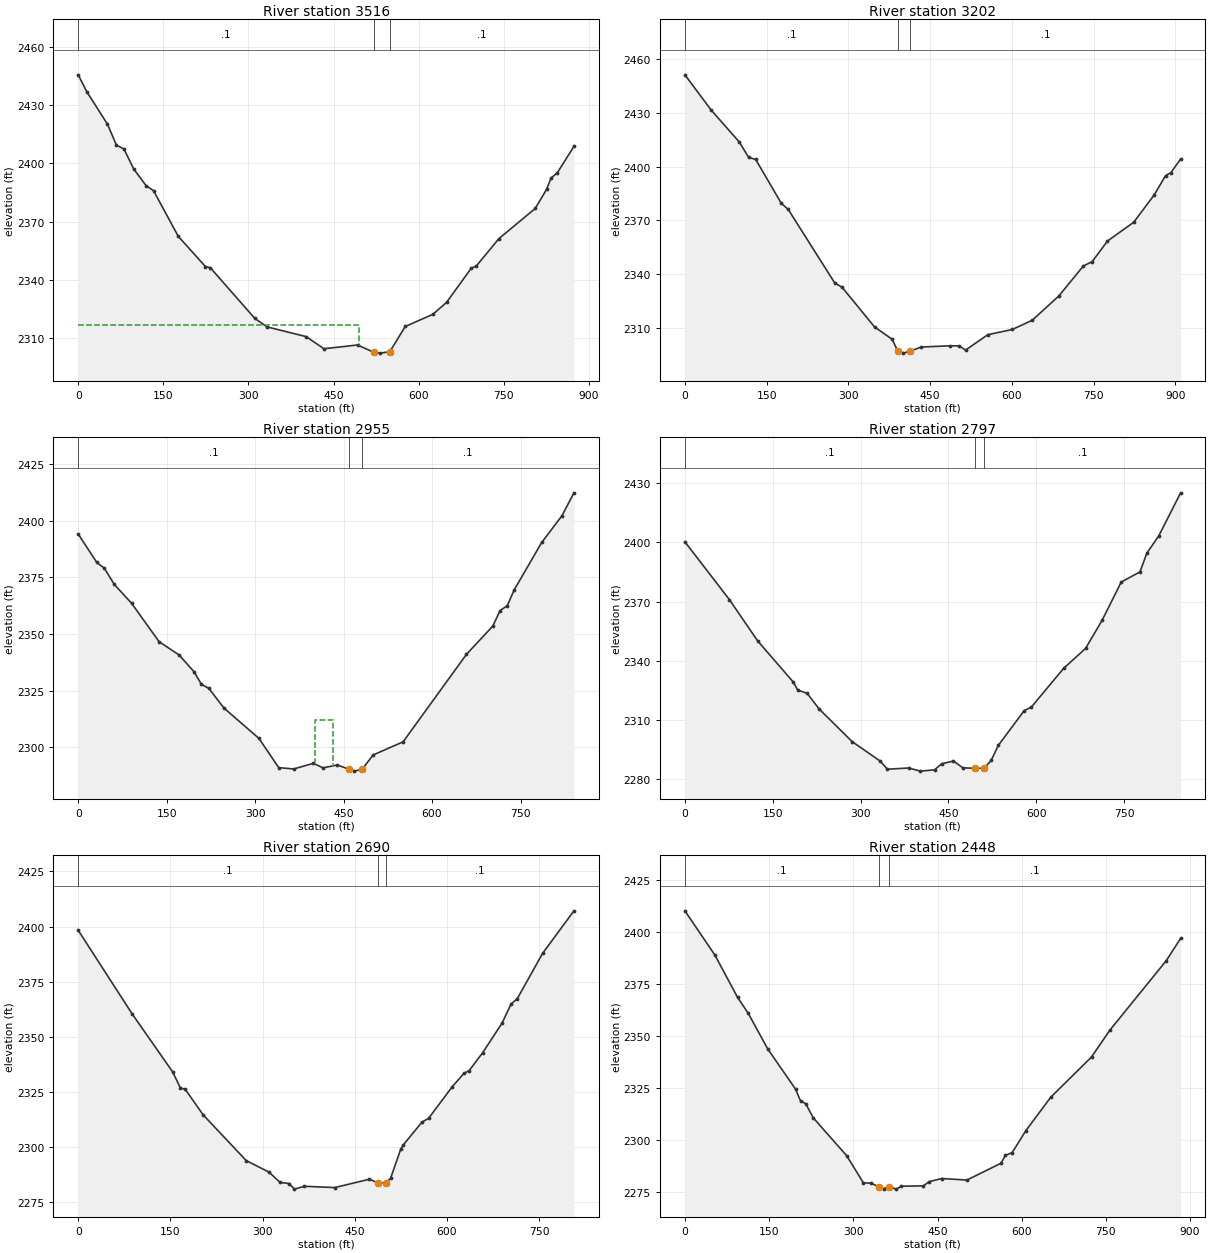
Type RM Length L Ch R = 1 ,3516    ,313.3,313.3,313.3
XS GIS Cut Line= 4
2203458.19916285634407.4330563482203901.56042692634597.627002519
2203991.88424387634601.7736013132204292.47000896634610.988931502
#Sta/Elev= 30
       0 2445.65      15 2437.01    51.6 2420.19    67.4 2409.39    80.5 2407.45
    97.9 2397.09   119.7 2388.48   132.7 2385.94   176.3  2362.4   224.1 2346.82
   232.8  2346.2   311.2 2320.07   332.9 2315.68   401.8 2310.67     433 2304.42
   492.2 2306.36   521.1 2302.58   531.8 2302.16   549.1 2302.88   576.4 2315.91
   625.2 2322.19   649.2 2328.35   692.9 2346.04   701.2 2346.96   741.2 2361.14
   805.3 2376.73   825.3 2386.54   833.3 2392.42   844.4 2395.18   873.6 2408.77
#Mann= 3 ,-1,0
       0      .1       0   521.1    .045       0   549.1      .1       0
#XS Ineff= 2 , 0
          494.58 2316.83
Permanent Ineff=
       F       F
Bank Sta=521.1,549.1
XS Rating Curve= 0 ,0
Exp/Cntr(USF)=0,0
Exp/Cntr=0.3,0.1

Type RM Length L Ch R = 1 ,3202    ,247.9,247.9,247.9
XS GIS Cut Line= 3
2203372.03378684634569.0914078782203462.37532216634684.309597844
2204211.29355694634830.950930528
#Sta/Elev= 30
       0 2451.02    48.6 2431.26    99.9 2413.62     117 2405.05   129.9 2403.93
   176.8 2379.59   189.6 2376.13   274.8 2335.29   288.4 2332.84     348 2310.76
   380.6 2303.85   390.52297.276   400.7 2296.19   413.2 2297.29   433.6 2299.58
   486.1 2300.27   502.9 2300.24   515.1 2297.89   555.8 2306.45   600.7 2309.34
   637.4 2314.49   686.3 2328.05   731.1 2344.66   747.4 2347.12   775.4 2358.56
   823.6 2369.02   861.1 2384.21   881.9  2394.9   891.8 2396.62   909.6 2404.21
#Mann= 3 ,-1,0
       0      .1       0   390.5    .045       0   413.2      .1       0
Bank Sta=390.5,413.2
XS Rating Curve= 0 ,0
Exp/Cntr(USF)=0,0
Exp/Cntr=0.3,0.1

Type RM Length L Ch R = 1 ,2955    ,157.3,157.3,157.3
XS GIS Cut Line= 4
2203306.35610635634834.7763708352203680.12419268634962.029623559
2203803.84782662634982.0886016382204119.64272401 635036.07422327
#Sta/Elev= 30
       0 2394.18    31.5  2381.6    44.2  2379.1    61.1 2371.92    90.7  2363.5
   137.1 2346.59   170.9 2340.74   196.3 2333.34     209 2327.73   221.6 2325.93
     247 2317.28   306.6  2303.8     340 2290.92   365.3 2290.32   398.9 2292.82
   415.1 2290.82   439.5 2292.09458.75582290.231   467.8 2289.37   481.3 2290.14
   500.2 2296.53   550.9 2302.31   658.3 2340.96   703.1  2353.5   715.3 2360.32
   727.5 2362.49   739.6 2369.61     786 2390.45   820.3 2402.25   840.6 2412.37
#Mann= 3 ,-1,0
       0      .1       0458.7558    .045       0   481.3      .1       0
#XS Ineff= 1 ,-1
  400.73  431.69 2312.14
Permanent Ineff=
       F
Bank Sta=458.7558,481.3
XS Rating Curve= 0 ,0
Exp/Cntr(USF)=0,0
Exp/Cntr=0.3,0.1

Type RM Length L Ch R = 1 ,2797    ,107.4,107.4,107.4
XS GIS Cut Line= 2
2203232.81180731635071.2797813152204073.38087501635169.477102309
#Sta/Elev= 30
       0 2400.31    75.9 2371.07   124.2 2350.13   184.6 2329.42   192.7 2325.23
   208.8 2323.54   228.9 2315.72   285.3 2299.15   333.6  2289.2   345.7 2285.13
   381.9 2285.73   402.1 2284.15   426.2  2284.8   438.3 2287.89   458.5 2289.25
   474.6 2285.81   495.2 2285.61   510.8 2285.61   522.9 2289.57     535 2297.19
   579.3 2314.81   591.4 2316.58   646.6 2336.22     684 2346.31   712.2 2360.53
   744.9 2379.93   776.9 2385.09   788.7  2394.6   808.9 2403.27   846.3 2425.13
#Mann= 3 ,-1,0
       0      .1       0   495.2    .045       0   510.8      .1       0
Bank Sta=495.2,510.8
XS Rating Curve= 0 ,0
Exp/Cntr(USF)=0,0
Exp/Cntr=0.3,0.1

Type RM Length L Ch R = 1 ,2690    ,242.2,242.2,242.2
BEGIN DESCRIPTION:
IFA to wet channel
END DESCRIPTION:
XS GIS Cut Line= 2
2203238.98669925635115.5213186362204021.65571695635311.915960623
#Sta/Elev= 30
       0  2398.3    87.8 2360.39   153.8 2334.05   166.2 2326.88   174.4 2326.12
   203.3 2314.62   273.4 2293.88   310.5 2288.63   328.7 2283.94   343.5 2283.46
   351.8 2280.91   368.3 2282.19   417.7 2281.62   473.8 2285.39   487.9 2283.81
   500.4 2283.69   508.5 2285.84     525 2299.04   529.1 2300.95   559.5 2311.28
   570.3 2313.01   608.9 2327.38   628.1 2333.49   636.3 2334.63   658.4  2342.8
   689.9 2356.18   704.6 2364.87   714.7 2367.29   755.9 2387.83   806.9 2407.12
#Mann= 3 ,-1,0
       0      .1       0   487.9    .045       0   500.4      .1       0
Bank Sta=487.9,500.4
XS Rating Curve= 0 ,0
Exp/Cntr(USF)=0,0
Exp/Cntr=0.3,0.1

Type RM Length L Ch R = 1 ,2448    ,299,299,299
XS GIS Cut Line= 3
2203204.57077864635165.0700883762203651.04126476635392.887873081
2204029.42827499635443.950479998
#Sta/Elev= 30
       0 2410.15    53.3 2388.94    93.9 2368.52   112.8 2360.89   147.7 2343.69
   197.1 2324.42   206.1 2318.68   215.1 2317.46   228.6 2310.64   288.2  2292.4
   317.9  2279.4   331.9 2279.17  346.072277.372   354.3 2276.44     3632277.586
   376.8 2276.33   385.8 2277.74     425 2277.91   435.1 2279.92   457.6 2281.43
   502.4  2280.7     563 2288.77     571 2292.53   583.1 2293.93   607.3 2304.42
   651.7 2320.51   724.4 2339.89   756.7 2352.65   857.6 2386.22   883.1 2396.92
#Mann= 3 ,-1,0
       0      .1       0  346.07    .045       0     363      .1       0
Bank Sta=346.07,363
XS Rating Curve= 0 ,0
Exp/Cntr(USF)=0,0
Exp/Cntr=0.3,0.1

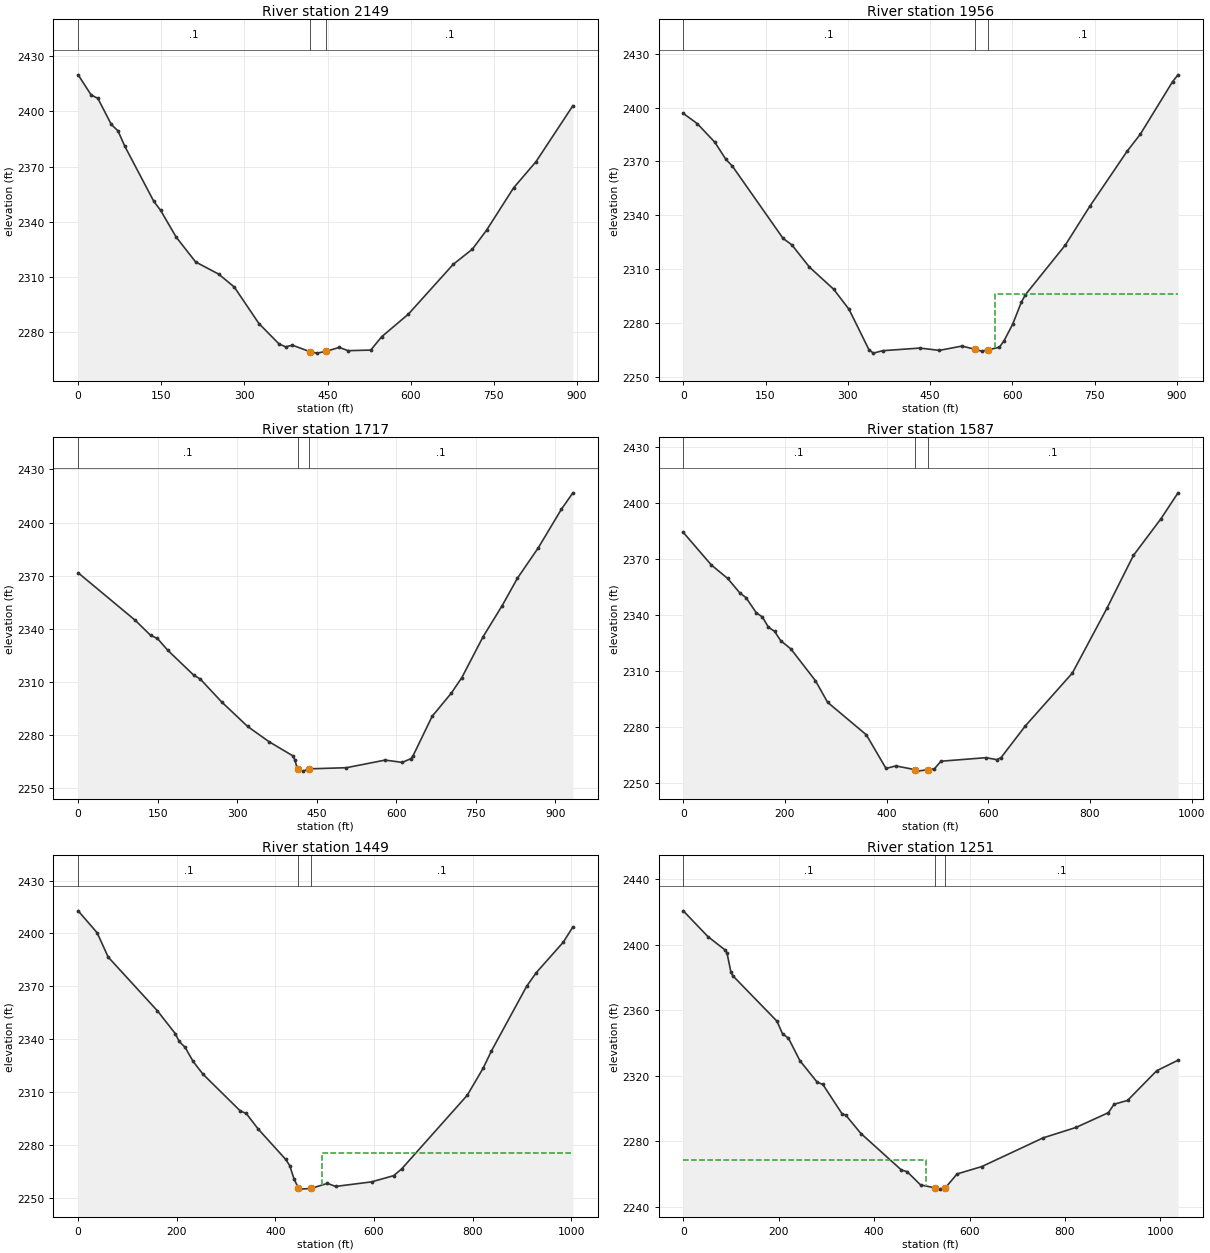
Type RM Length L Ch R = 1 ,2149    ,193,193,193
XS GIS Cut Line= 4
2203104.93707374635549.7553202012203443.75420055635595.871691689
2203660.07926176 635573.32267724 2203990.0222603635620.457391317
#Sta/Elev= 30
       0 2419.89    23.5 2408.92    35.6 2407.07    59.8 2392.91    71.9 2389.42
      84 2381.16   136.5 2351.09   148.6 2346.28   176.9 2331.64     212 2318.13
   253.6 2311.51   281.8 2304.47   326.2 2284.64   362.5 2273.54   374.5 2271.98
   386.6 2272.87   417.6 2269.43   430.8 2268.55   446.8 2269.47   471.1 2271.67
   487.1 2269.89     528 2270.21   547.5 2277.41   595.9 2289.77   676.7 2316.81
   711.4  2325.1   737.3 2335.57   785.8 2358.46   826.2 2372.68   892.7 2403.09
#Mann= 3 ,-1,0
       0      .1       0   417.6    .045       0   446.8      .1       0
Bank Sta=417.6,446.8
XS Rating Curve= 0 ,0
Exp/Cntr(USF)=0,0
Exp/Cntr=0.3,0.1

Type RM Length L Ch R = 1 ,1956    ,238.7,238.7,238.7
XS GIS Cut Line= 5
2203074.82322864635705.561736178 2203396.3725358635730.828523854
2203584.41247449635755.8126776352203811.77157756635776.376113331
2203972.49895226635791.422692693
#Sta/Elev= 30
       0 2396.77    25.4 2391.08    57.5 2380.69    77.6 2371.16    89.6 2367.33
   181.9 2327.09     198 2323.47   230.1 2311.04   274.2 2298.73   302.3 2287.49
   338.5 2265.02   346.6 2263.12   363.6 2264.48   431.3 2265.94   466.9 2264.66
     508 2267.05   532.1 2265.24   544.1 2264.25   556.2 2264.96   576.3 2266.43
   584.3 2269.74   600.4 2279.13   616.4 2291.55   623.8 2295.71   696.7 2323.43
   740.9 2344.86   809.2 2375.68   833.2 2385.13   892.2  2414.5     902 2418.26
#Mann= 3 ,-1,0
       0      .1       0   532.1    .045       0   556.2      .1       0
#XS Ineff= 2 , 0
                          568.31         2296.31
Permanent Ineff=
       F       F
Bank Sta=532.1,556.2
XS Rating Curve= 0 ,0
Exp/Cntr(USF)=0,0
Exp/Cntr=0.3,0.1

Type RM Length L Ch R = 1 ,1717    ,129.9,129.9,129.9
XS GIS Cut Line= 3
2203025.06991933635844.3472831822203652.22347608635949.091092242
2203949.43403429635935.998116109
#Sta/Elev= 30
       0 2371.69   107.7 2344.88     137 2336.31   149.4 2334.66   169.4 2327.86
   218.1  2313.9   230.3 2311.76   270.8 2298.78   319.6 2285.01     360 2276.39
   404.6 2268.47   408.7 2266.16   412.7 2261.95  415.022260.909   423.9 2259.76
   436.1 2261.05     506 2261.69     579 2265.99   611.5 2264.69   627.7 2266.82
   631.7 2268.37   667.8  2290.7   703.9 2303.76   723.9 2312.59   763.9 2335.62
     800 2353.21   828.5 2368.54     868 2385.78   911.8 2407.64   933.3 2416.82
#Mann= 3 ,-1,0
       0      .1       0  415.02    .045       0   436.1      .1       0
Bank Sta=415.02,436.1
XS Rating Curve= 0 ,0
Exp/Cntr(USF)=0,0
Exp/Cntr=0.3,0.1

Type RM Length L Ch R = 1 ,1587    ,137.6,137.6,137.6
XS GIS Cut Line= 4
2202997.13823692635980.6597124722203376.83454476636009.755214989
2203609.59856489636088.3130717842203955.83504484636069.400995148
#Sta/Elev= 30
       0 2384.12    55.2 2366.68    87.3  2359.5   111.4 2351.69   123.4 2349.24
   143.5 2341.14   155.5 2338.91   167.5  2333.4   179.6 2331.19   191.6 2326.21
   211.7 2321.77   259.8 2304.86   283.9 2293.24   360.1 2275.83   398.8 2257.84
   418.1 2259.21   455.6 2257.19   460.3 2256.41   481.4 2257.18   494.1 2257.68
   506.8 2261.71   595.4 2263.61   616.6 2262.56     625 2263.62   673.1 2280.68
   765.3 2308.86   833.4 2343.55   885.4 2371.77   939.5 2391.38   973.2 2405.29
#Mann= 3 ,-1,0
       0      .1       0   455.6    .045       0   481.4      .1       0
Bank Sta=455.6,481.4
XS Rating Curve= 0 ,0
Exp/Cntr(USF)=0,0
Exp/Cntr=0.3,0.1

Type RM Length L Ch R = 1 ,1449    ,199,199,199
XS GIS Cut Line= 5
2202959.31408365636175.5995793342203396.36399809636166.193787913
2203449.16765532636160.5067903952203606.27458428636129.901249166
2203957.28981997636092.677397161
#Sta/Elev= 30
       0 2412.86    38.5 2400.41    60.9  2386.6   160.9 2356.03   196.9 2343.16
   204.9 2338.69   216.9 2335.35   232.9 2327.46   252.9 2320.16   328.9 2299.19
   340.9 2297.79   364.9 2289.01     421 2271.67     429  2268.2   437.9 2260.51
   446.6 2255.51     449 2254.82472.52352255.219   505.5  2258.1   521.9 2256.35
   595.2 2258.95     640 2262.48   656.3 2266.37     789 2308.11   821.2 2323.43
   838.2 2333.33   909.7 2370.09   929.1 2377.78   983.7 2395.02  1003.3  2403.7
#Mann= 3 ,-1,0
       0      .1       0   446.6    .045       0472.5235      .1       0
#XS Ineff= 2 , 0
                          493.99         2275.62
Permanent Ineff=
       F       F
Bank Sta=446.6,472.5235
XS Rating Curve= 0 ,0
Exp/Cntr(USF)=0,0
Exp/Cntr=0.3,0.1

Type RM Length L Ch R = 1 ,1251    ,114.4,114.4,114.4
XS GIS Cut Line= 2
2202944.76633239636300.7102401552203977.65667173636392.361073083
#Sta/Elev= 30
       0 2420.77    51.6 2405.05    87.8 2396.83    91.8 2394.78    99.8 2383.37
   103.8 2381.14   196.2 2353.46   208.2 2345.61   220.3 2343.09   244.4 2329.32
   280.5 2316.23   292.6 2314.78   332.7 2296.93   340.7 2296.02   372.4 2284.84
   457.1 2262.59   469.2 2261.55   497.4 2253.46  526.762251.772   537.5 2250.91
   549.5 2251.79   573.7 2260.16   625.9 2264.71   754.4 2282.22   822.9 2288.54
   890.9 2297.56   902.9 2302.72   931.1 2305.03   992.1 2323.14  1036.9  2329.6
#Mann= 3 ,-1,0
       0      .1       0  526.76    .045       0   549.5      .1       0
#XS Ineff= 2 , 0
          507.73 2268.97
Permanent Ineff=
       F       F
Bank Sta=526.76,549.5
XS Rating Curve= 0 ,0
Exp/Cntr(USF)=0,0
Exp/Cntr=0.3,0.1

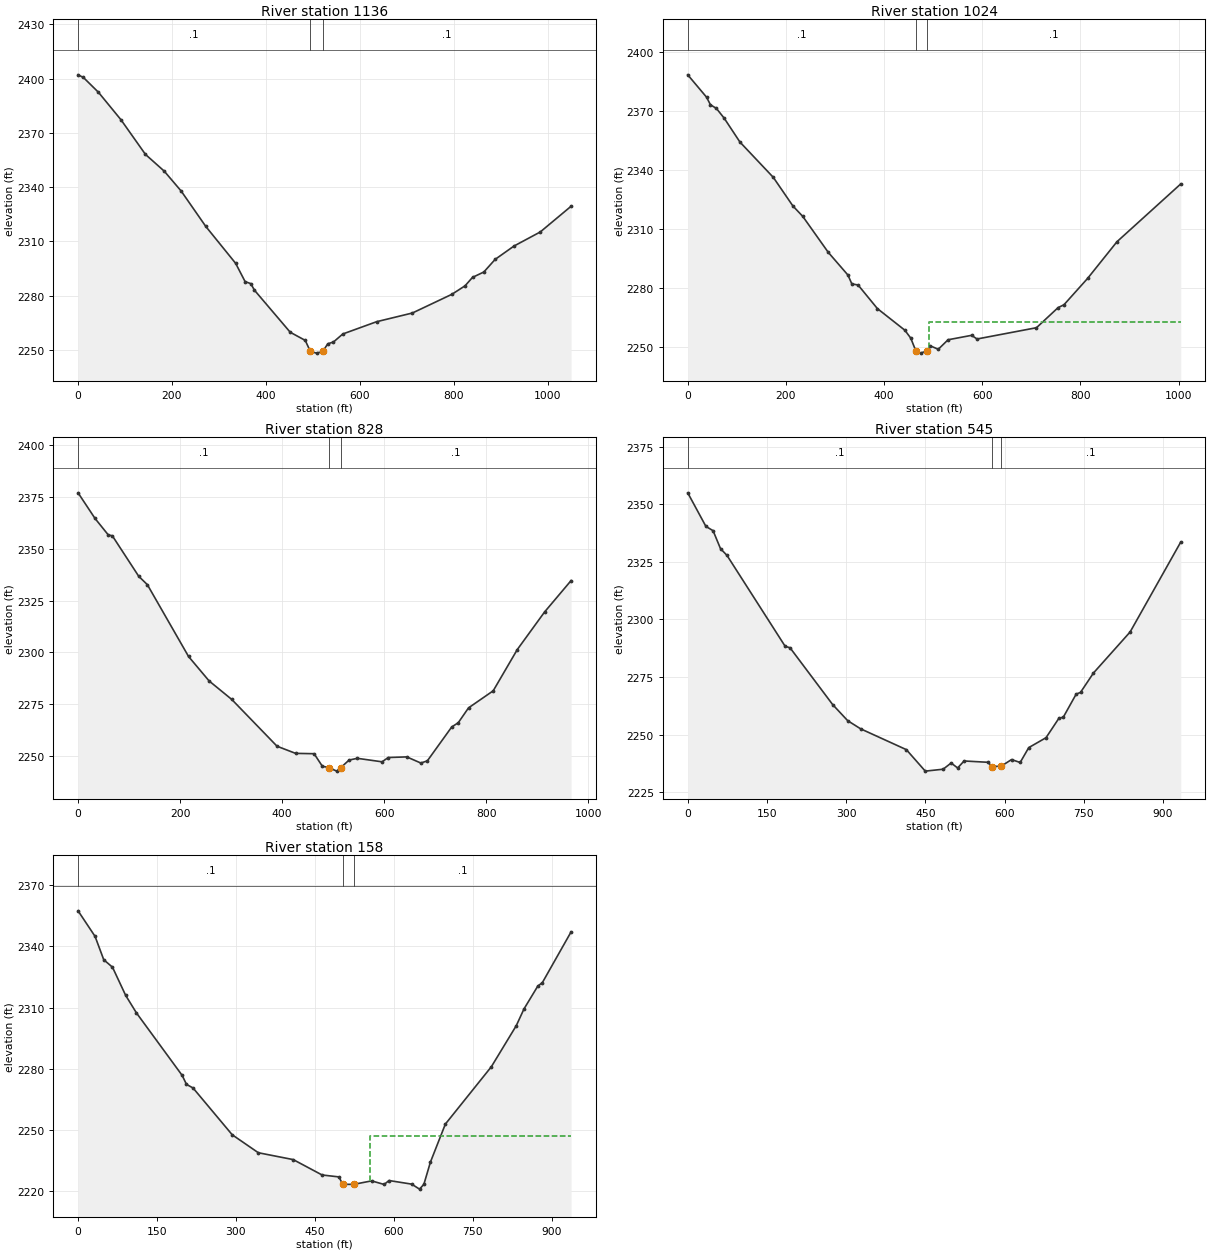
Type RM Length L Ch R = 1 ,1136    ,112.6,112.6,112.6
XS GIS Cut Line= 2
  2202940.838604636437.0423560112203989.75189358636482.123653824
#Sta/Elev= 30
       0 2402.09    11.3 2400.64    43.4 2392.44    91.4 2377.24   143.5 2358.11
   183.5 2348.85   219.5 2337.88     272 2318.29   335.6 2297.89   355.7  2287.8
   367.7 2286.69   375.7 2283.03   451.8 2259.81   483.8  2255.3   494.72249.205
   507.8 2248.27  521.05 2249.21   531.8 2253.43   543.8 2254.41   563.8 2258.86
   635.9 2265.65     712 2270.45   796.1 2280.79   824.1 2285.48     840 2290.14
   864.1 2293.11   888.2 2300.09   928.2 2307.44   984.2 2315.23  1049.9 2329.45
#Mann= 3 ,-1,0
       0      .1       0   494.7    .045       0  521.05      .1       0
Bank Sta=494.7,521.05
XS Rating Curve= 0 ,0
Exp/Cntr(USF)=0,0
Exp/Cntr=0.3,0.1

Type RM Length L Ch R = 1 ,1024    ,195.7,195.7,195.7
XS GIS Cut Line= 2
 2202965.9077373636563.1427907372203970.04317741636578.551518718
#Sta/Elev= 30
       0 2388.46    38.3 2377.11    46.3 2373.24    58.3 2371.42    74.3 2366.42
   106.3 2354.33   174.3 2336.38   214.3 2321.83   234.3 2316.57   286.3 2298.29
   326.3 2286.78   334.3 2282.28     347 2281.72   386.3 2269.75   442.3 2258.75
   454.3 2254.73  464.542248.308   474.3 2247.12  487.942248.334   494.3 2250.81
   510.3 2249.07   530.3 2253.91   578.3 2256.16   589.3  2254.3   710.4 2260.03
   754.4 2270.23   766.4 2271.69   814.4 2285.03   874.4 2303.71  1004.3 2333.05
#Mann= 3 ,-1,0
       0      .1       0  464.54    .045       0  487.94      .1       0
#XS Ineff= 2 , 0
                           491.8          2262.8
Permanent Ineff=
       F       F
Bank Sta=464.54,487.94
XS Rating Curve= 0 ,0
Exp/Cntr(USF)=0,0
Exp/Cntr=0.3,0.1

Type RM Length L Ch R = 1 ,828     ,283.3,283.3,283.3
XS GIS Cut Line= 2
2203009.56579992636819.9549237582203967.47505608636694.116978578
#Sta/Elev= 30
       0 2377.07    33.3 2364.66    59.1 2356.75    67.2 2356.28   118.9 2336.71
   135.8 2332.66   216.5 2297.94   256.8 2286.12   301.2 2277.17   389.9 2254.56
   426.2 2251.11   462.5 2250.94   478.7 2244.88   490.8 2244.27   506.9 2242.52
     515 2244.27   531.1 2247.88   547.3 2248.71   595.7 2247.02   607.8  2249.1
   644.1  2249.4   671.6 2246.44   684.4 2247.48   732.2 2263.87     745 2265.92
   765.1  2273.1   813.5 2281.36   860.6 2301.27   914.1 2319.45   966.1 2334.65
#Mann= 3 ,-1,0
       0      .1       0   490.8    .045       0     515      .1       0
Bank Sta=490.8,515
XS Rating Curve= 0 ,0
Exp/Cntr(USF)=0,0
Exp/Cntr=0.3,0.1

Type RM Length L Ch R = 1 ,545     ,386,386,386
XS GIS Cut Line= 2
2203083.32952363637084.9338840072203998.21123034 636898.05255977
#Sta/Elev= 30
       0 2354.94    34.4 2340.37      48  2338.5    62.1 2330.69    74.3  2327.8
   184.6 2288.29   193.7  2287.7   274.4 2263.05     303 2256.03   327.5  2252.5
   414.1 2243.46   449.9 2234.14   483.7 2234.97   498.9 2237.67   511.2 2235.51
   523.4 2238.55   568.3 2237.98   576.5 2236.12  593.822236.315   613.3 2239.16
   629.6 2237.89   645.9 2244.35   678.6 2248.65   703.1 2257.12   711.2 2257.51
   735.7 2267.57   743.9 2268.31   768.4 2276.72   837.9 2294.55   933.8 2333.59
#Mann= 3 ,-1,0
       0      .1       0   576.5    .045       0  593.82      .1       0
Bank Sta=576.5,593.82
XS Rating Curve= 0 ,0
Exp/Cntr(USF)=0,0
Exp/Cntr=0.3,0.1

Type RM Length L Ch R = 1 ,158     ,,,
XS GIS Cut Line= 3
2203180.95409599637380.5968745912203825.27627359 637210.45119133
2204056.78597376637070.987516526
#Sta/Elev= 30
       0 2357.35    32.3 2344.83    48.8 2333.39    65.4 2329.74    90.5 2315.91
   110.9 2307.36   197.8 2276.74     206 2272.36   218.5 2270.58   292.9 2247.67
   342.5 2238.88   408.8 2235.52   463.6 2227.99   495.6 2227.04   502.9 2223.38
     5242223.413   557.7  2225.1   581.5 2223.35   590.8 2225.27   633.8 2223.51
   648.7 2221.06     657  2223.4   669.4 2234.26   697.8  2252.9   785.2    2281
   832.6 2301.13   847.2 2309.31   873.4 2320.47   882.2 2322.23   936.7 2347.05
#Mann= 3 ,-1,0
       0      .1       0   502.9    .045       0     524      .1       0
#XS Ineff= 2 , 0
                          553.73         2246.97
Permanent Ineff=
       F       F
Bank Sta=502.9,524
XS Rating Curve= 0 ,0
Exp/Cntr(USF)=0,0
Exp/Cntr=0.3,0.1
LCMann Table=0

Chan Stop Cuts=-1
Use User Specified Reach Order=0
Composite Channel Slope=5